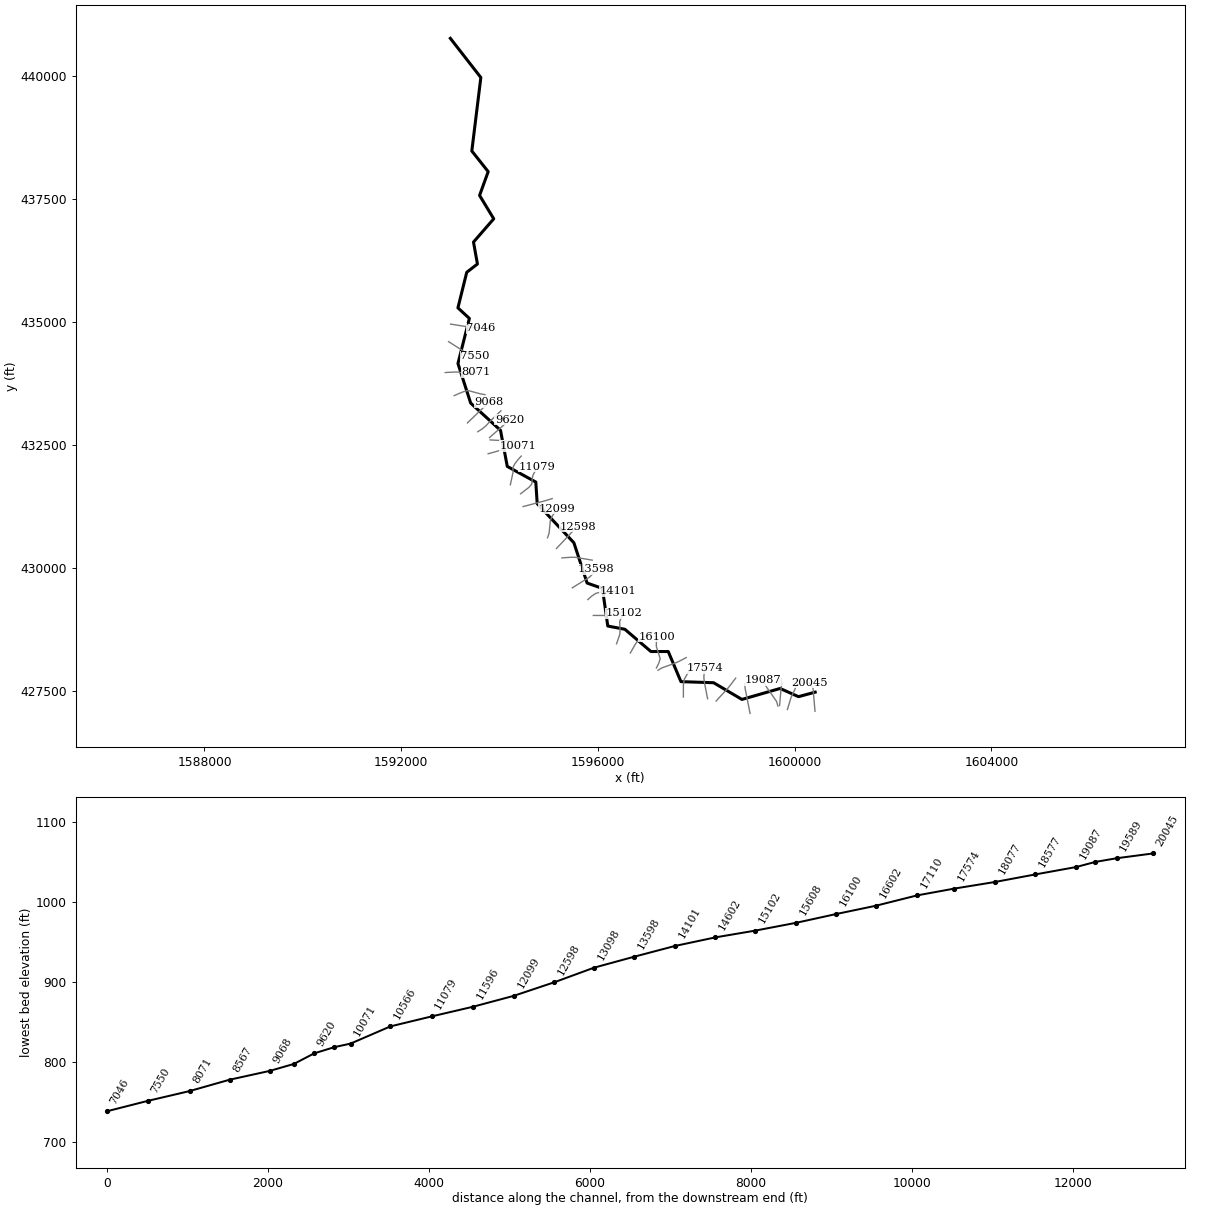
--- HAYNESRN.prj (project) ---

Proj Title=HAYNESRN
Current Plan=p01
Default Exp/Contr=0,0
English Units
Geom File=g01
Flow File=f01
Plan File=p01
BEGIN DESCRIPTION:
---------- MODELED AS PART OF WVEMD CTP PROGRAM, 2023----------
Stream Name: Haynes Run
Flood Zone:  AFH
Wetzel County, WV
HEC-RAS Version: RAS 6.3
Vertical Datum: NAVD88
Projection: NAD 1983 StatePlane West Virginia S FIPS 4702 (US Feet)
Terrain: 1-meter West Virginia FEMA R3 South Central (collected 2018-2020)
Land Use: 2019 NLCD
Hydrologic Method:
WV 2010 Regional Regression Equations
Additional Model Notes:
None
END DESCRIPTION:
DSS Export Rating Curves= 0
DSS Export Rating Curve Sorted= 0
DSS Export Volume Flow Curves= 0
DXF OffsetX= 0
DXF OffsetY= 0
DXF ScaleX= 0
DXF ScaleY= 0

--- HAYNESRN.p01 (plan) ---

Plan Title=Floodplain
Program Version=6.30
Short Identifier=Floodplain
Geom File=g01
Flow File=f01
Subcritical Flow
K Sum by GR= 0
Std Step Tol= 0.01
Critical Tol= 0.01
Num of Std Step Trials= 20
Max Error Tol= 0.3
Flow Tol Ratio= 0.001
Split Flow NTrial= 30
Split Flow Tol= 0.02
Split Flow Ratio= 0.02
Log Output Level= 0
Friction Slope Method= 1
Unsteady Friction Slope Method= 2
Unsteady Bridges Friction Slope Method= 1
Parabolic Critical Depth
Global Vel Dist= 0 , 0 , 0
Global Log Level= 0
CheckData=True
Encroach Param=-1 ,0,0, 0
Mapping Interval=1HOUR
Computation Time Step Use Courant=        0
Computation Time Step Use Time Series=    0
Computation Time Step Count To Double=0
Computation Time Step Max Doubling=0
Computation Time Step Max Halving=0
Computation Time Step Residence Courant=0
Run HTab= 0
Run UNet= 0
Run Sediment= 0
Run PostProcess= 0
Run WQNet= 0
Run RASMapper= 0
UNET Theta= 0
UNET Theta Warmup= 0
UNET ZTol= 0
UNET ZSATol= 0
UNET MxIter= 0
UNET Max Iter WO Improvement= 0
UNET MaxInSteps= 0
UNET DtIC= 0
UNET DtMin= 0
UNET MaxCRTS= 0
UNET WFStab= 0
UNET SFStab= 0
UNET WFX= 1
UNET SFX= 1
UNET Gravity=32.17405
UNET 1D Methodology=Finite Difference
UNET DSS MLevel= 1
UNET Pardiso=0
UNET DZMax Abort= 0
UNET Use Existing IB Tables= 0
UNET Froude Reduction=False
UNET Froude Limit= 0
UNET Froude Power= 0
UNET D1 Cores= 0
UNET WindReference=Eulerian
UNET WindDragFormulation=Hsu (1988)
UNET D2 Coriolis=0
UNET D2 Cores= 0
UNET D2 Theta= 1
UNET D2 Theta Warmup= 1
UNET D2 Z Tol= 0.01
UNET D2 Volume Tol= 0.01
UNET D2 Max Iterations= 20
UNET D2 Equation= 0
UNET D2 RampUpFraction=0.1
UNET D2 TimeSlices= 1
UNET D2 Turbulence Formulation=Non-Conservative (original)
UNET D2 Eddy Viscosity=0.3
UNET D2 Transverse Eddy Viscosity=0.1
UNET D2 Smagorinsky Mixing=0
UNET D2 BCVolumeCheck=0
UNET D2 Cores=0
UNET D2 SolverType=PARDISO (Direct)
UNET D2 Minimum Iterations= 3
UNET D2 Maximum Iterations= 30
UNET D2 Restart Number= 10
UNET D2 Relaxation Coeff=1.3
UNET D2 SOR Precondition Iterations= 10
UNET D2 ILUT Maximum Fill= 8
UNET D2 ILUT Tolerance=1E-08
UNET D2 Convergence Tolerance=0.00001
UNET D1D2 MaxIter= 0
UNET D1D2 ZTol=0.01
UNET D1D2 QTol=0.1
UNET D1D2 MinQTol=1
Write IC File= 0
Write IC File at Fixed DateTime=0
Write IC File at Sim End=0
Echo Input=False
Echo Parameters=False
Echo Output=False
Write Detailed= 0
HDF Write Warmup=0
HDF Write Time Slices=0
HDF Flush=0
HDF Compression= 1
HDF Chunk Size= 1
HDF Spatial Parts= 1
HDF Use Max Rows=0
HDF Fixed Rows= 1
Calibration Method= 0
Calibration Iterations= 20
Calibration Max Change=0.05
Calibration Tolerance=0.2
Calibration Maximum=1.5
Calibration Minimum=0.5
Calibration Optimization Method= 1
WQ AD Non Conservative
WQ ULTIMATE=-1
WQ Max Comp Step=1HOUR
WQ Output Interval=15MIN
WQ Output Selected Increments= 0
WQ Output face flow=0
WQ Output face velocity=0
WQ Output face area=0
WQ Output face dispersion=0
WQ Output cell volume=0
WQ Output cell surface area=0
WQ Output cell continuity=0
WQ Output cumulative cell continuity=0
WQ Output face conc=0
WQ Output face dconc_dx=0
WQ Output face courant=0
WQ Output face peclet=0
WQ Output face adv mass=0
WQ Output face disp mass=0
WQ Output cell mass=0
WQ Output cell source sink temp=0
WQ Output nsm pathways=0
WQ Output nsm derived pathways=0
WQ Create Restart=0
WQ Fixed Restart=0
WQ System Summary=0
WQ Write To DSS=0
Sorting and Armoring Iterations= 10
XS Update Threshold= 0.02
Bed Roughness Predictor= 0
Hydraulics Update Threshold= 0.02
Energy Slope Method= 1
Volume Change Method= 1
Sediment Retention Method= 0
Sediment TS Multiplier= 1
Warm Up Method= 0
XS Weighting Method= 0
Number of US Weighted Cross Sections= 1
Number of DS Weighted Cross Sections= 1
Upstream XS Weight=0
Main XS Weight=1
Downstream XS Weight=0
Number of DS XS's Weighted with US Boundary= 1
Upstream Boundary Weight= 1
Weight of XSs Associated with US Boundary= 0
Number of US XS's Weighted with DS Boundary= 1
Downstream Boundary Weight= 0.5
Weight of XSs Associated with DS Boundary= 0.5
Percentile Method= 0
Sediment Output Level= 3
Mass or Volume Output= 0
Output Increment Type= 1
Profile and TS Output Increment= 1
Transport Output Increment 1
XS Output Flag= 0
XS Output Increment= 10
Read HDF5 Sediment Hotstart= 0
Sediment Hotstart Type= 0
Write Gradation File= 0
Read Gradation Hotstart= 0
Write HDF5 File= 1
Write Binary Output= 1
Write DSS Sediment File= 0
DSS Sediment Output Type= 1
SV Curve= 0
Specific Gage Flag= 0
Subcell Erosion Methods= 0
Subcell Deposition Methods= 0
Advection Scheme= 1
Matrix Solver= 0
Implicit Weighting Factor= 1
Maximum Outer Loop Convergence Iterations= 5
Convergence Maximum Absolute= 0.001
Convergence RMSE= 0.0001
Grain Fractions Max Abs Error= 0.001
Max Subgrid Regions= 1
Max Subgrid Length Scale= 3.402823E+38
Initial Layer Thickness= 3.402823E+38
Min Layer Thickness= 3.402823E+38
Max Layer Thickness= 3.402823E+38
Number of Layers= 5

--- HAYNESRN.f01 (steady flow) ---

Flow Title=Flow
Program Version=6.31
Number of Profiles= 1
Profile Names=F01pct
River Rch & RM=HAYNESRN,Main,20045
     600
River Rch & RM=HAYNESRN,Main,18577
     711
River Rch & RM=HAYNESRN,Main,16602
     894
River Rch & RM=HAYNESRN,Main,13598
     996
River Rch & RM=HAYNESRN,Main,10566
    1110
River Rch & RM=HAYNESRN,Main,9367
    1250
River Rch & RM=HAYNESRN,Main,4496
    1420
Boundary for River Rch & Prof#=HAYNESRN,Main            , 1
Up Type= 0
Dn Type= 3
Dn Slope=0.00717
DSS Import GetInterval= 0
DSS Import GetPeak= 0
DSS Import FillOption= 0

--- HAYNESRN.g01 (geometry) ---

Geom Title=Geometry
Program Version=6.30

River Reach=HAYNESRN        ,Main
Reach XY= 30
1600415.86464533427467.5409526111600076.37753891427375.680845817
 1599703.1734131 427542.55279637     1598926.784      427319.559
1598351.01335928427659.1961268031597686.77872045427681.241524494
     1597428.614      428293.531      1597076.56      428293.531
     1596546.538      428745.894     1596199.118       428811.49
     1596090.292      429576.198     1595779.009      429685.567
     1595509.791      430505.5161594764.21470659431300.170331623
1594735.68031681      431739.335     1594155.549      432057.426
1594018.51486305432790.437423758     1593411.706      433344.597
1593153.25878866434148.5748943311593385.29125138435065.855695934
 1593152.4092719435280.385395298     1593331.661      436003.323
     1593549.065      436172.191     1593469.182      436618.123
     1593880.734      437091.357     1593592.546      437566.614
     1593768.002      438049.865     1593434.932      438469.799
     1593618.447      439964.074     1592998.458      440760.247

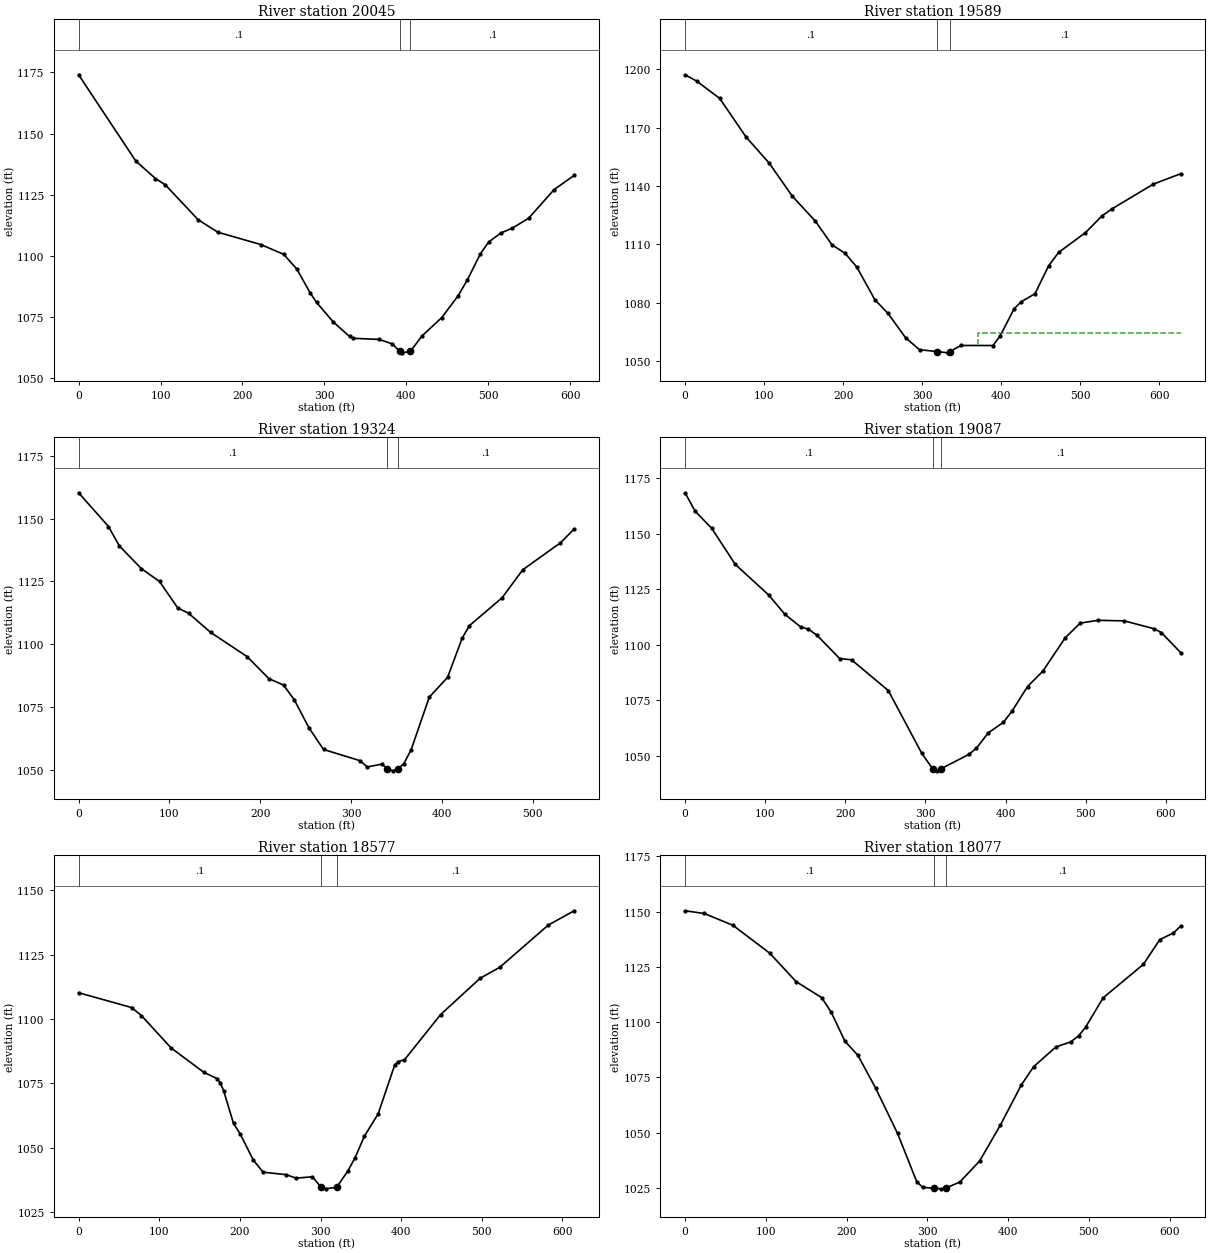
Type RM Length L Ch R = 1 ,20045   ,462.2,456,453.8
XS GIS Cut Line= 3
1600412.43920139 427079.052807341600372.10882368427551.814457225
1600293.68864479427656.001266323
#Sta/Elev= 30
       0 1174.05    69.7 1138.78    93.8  1131.6   105.9 1128.99     146 1114.69
   170.1 1109.61   222.3  1104.6   250.4 1100.56   266.4 1094.52   282.5 1084.89
   290.5 1080.87   310.6 1072.99   330.7 1066.97   334.8 1066.22   366.8 1065.77
   382.9 1063.93   391.9  1060.9   394.9 1060.27   405.1 1060.91     419 1067.14
   443.1 1074.64   463.2 1083.61   474.4 1090.02   490.4 1100.77   500.4 1105.57
   515.4  1109.3   529.3 1111.28   549.3 1115.34   580.5  1127.1   604.9 1132.88
#Mann= 3 ,-1,0
       0      .1       0   391.9    .045       0   405.1      .1       0
Bank Sta=391.9,405.1
XS Rating Curve= 0 ,0
Exp/Cntr(USF)=0,0
Exp/Cntr=0.3,0.1

Type RM Length L Ch R = 1 ,19589   ,263.3,265.8,267.5
XS GIS Cut Line= 6
1599850.99734458427114.669690669 1599925.5047415427360.292230919
1599969.12112409427453.0092370961600003.18864125427523.227600589
1600034.27781792427608.2809081671600048.27352484427706.685567006
#Sta/Elev= 30
       0  1197.1    14.5 1193.89    43.8 1184.96    77.2 1165.09   106.5 1151.67
   135.7  1134.7     165 1121.83   185.9 1109.71   202.6 1105.34   217.3 1098.28
   240.2 1081.48   256.7 1074.53     279 1061.98   296.7 1055.82   319.2 1054.89
   332.1 1054.23   335.2 1054.88     349 1058.02   389.7 1057.99   398.6  1062.9
   416.4 1076.88   425.3 1080.45   442.8  1084.6   459.9 1098.85   472.6 1105.81
   506.7    1116   527.7 1124.63   540.1 1128.18   592.6 1140.93   627.1 1146.25
#Mann= 3 ,-1,0
       0      .1       0   319.2    .045       0   335.2      .1       0
#XS Ineff= 2 , 0
                          370.83         1064.21
Permanent Ineff=
       F       F
Bank Sta=319.2,335.2
XS Rating Curve= 0 ,0
Exp/Cntr(USF)=0,0
Exp/Cntr=0.3,0.1

Type RM Length L Ch R = 1 ,19324   ,231.7,236.4,239.9
XS GIS Cut Line= 3
 1599691.8522118427195.7713630351599730.69858328427629.215086919
1599722.52039981427739.620563758
#Sta/Elev= 30
       0 1160.25    32.9 1146.83    44.9 1139.08      69 1130.11    89.1 1124.95
   109.2 1114.43   121.2 1112.29   145.3 1104.72   185.5 1095.08   209.6 1086.28
   225.8 1083.71   237.7 1077.79   253.8 1066.66   269.8  1058.1     310 1053.64
     318 1051.16   334.1 1052.26     340  1050.5   346.1  1049.6   352.31050.505
   358.2 1052.45   366.2 1057.89   386.3 1078.93   406.4 1086.77   422.5 1102.38
   430.5 1107.38   466.6  1118.5   489.2 1129.59   530.8 1140.36   545.9 1145.83
#Mann= 3 ,-1,0
       0      .1       0     340    .045       0   352.3      .1       0
Bank Sta=340,352.3
XS Rating Curve= 0 ,0
Exp/Cntr(USF)=0,0
Exp/Cntr=0.3,0.1

Type RM Length L Ch R = 1 ,19087   ,510.6,510.4,504.6
XS GIS Cut Line= 6
1599658.06662808 427184.509446011599630.88000268427278.582748666
1599480.78548659427493.9379610121599437.36923485427555.096959427
 1599392.0530525427630.4704963421599349.36055259427715.341389582
#Sta/Elev= 30
       0 1168.38    12.5  1160.1    33.3 1152.37    62.5  1136.2   104.2 1122.41
   124.7 1113.63   144.2 1108.03   153.9 1107.01   164.5  1104.3   192.9 1093.78
   207.7 1093.22   253.6 1079.38   295.3 1051.17  308.991044.155   313.9 1043.26
  319.141044.149   354.2 1050.67   363.6 1053.46   378.3 1060.34   397.2 1065.07
   407.8 1070.03   427.4  1081.2   446.4  1088.1   474.4 1103.15   493.1 1109.74
   515.5 1110.99   548.1 1110.74   585.5 1107.17   594.4 1105.46   618.4 1096.48
#Mann= 3 ,-1,0
       0      .1       0  308.99    .045       0  319.14      .1       0
Bank Sta=308.99,319.14
XS Rating Curve= 0 ,0
Exp/Cntr(USF)=0,0
Exp/Cntr=0.3,0.1

Type RM Length L Ch R = 1 ,18577   ,504,499.6,486.5
XS GIS Cut Line= 6
1599091.97524059  427036.07470351599073.78334785427128.043023512
1599056.80503534427213.8797940911599008.29397751427459.127991259
1598991.31468076427544.9647618381598983.31732142427640.530187503
#Sta/Elev= 30
       0  1110.2    65.7 1104.44    77.9 1101.32   114.6 1088.76   155.4 1079.22
   171.7 1076.82   175.8 1075.09   179.9 1072.04   192.1 1059.35   200.3 1055.33
   216.6 1045.15   228.8 1040.42   257.4 1039.45   269.6 1038.11     290 1038.62
   300.7 1034.55   306.3 1033.94  320.07 1034.58   333.9 1040.89     343 1046.12
   354.3 1054.37   371.5  1063.1   391.9 1081.99     396 1083.44   404.1 1084.12
     449 1101.72   497.9 1115.81   522.3 1120.08   582.5 1136.51   614.6 1142.07
#Mann= 3 ,-1,0
       0      .1       0   300.7    .045       0  320.07      .1       0
Bank Sta=300.7,320.07
XS Rating Curve= 0 ,0
Exp/Cntr(USF)=0,0
Exp/Cntr=0.3,0.1

Type RM Length L Ch R = 1 ,18077   ,498.1,503.7,508.9
XS GIS Cut Line= 6
1598401.87032159427286.9911964241598464.83804342427356.456280589
1598575.41164118427475.5351106671598642.88821226427549.342377752
1598689.71390601427608.2093860061598799.99682193427753.114936084
#Sta/Elev= 30
       0 1150.39    23.7 1149.16    59.3  1143.8   104.8 1131.19   137.5 1118.31
   169.1 1111.09     181 1104.41     198 1091.29     214 1084.95   235.8 1070.21
   263.1 1049.58   286.9 1027.71   294.3 1025.18  308.661024.821   317.2 1024.53
  322.781024.816   340.3 1027.65   364.7 1037.12   390.4 1053.38   416.3 1071.52
   431.5  1079.8   459.1 1088.75   477.3 1091.01   487.4 1093.83   496.2 1097.86
   517.6 1110.97   567.6 1126.19   587.8 1137.36   604.7 1140.35   613.6 1143.47
#Mann= 3 ,-1,0
       0      .1       0  308.66    .045       0  322.78      .1       0
Bank Sta=308.66,322.78
XS Rating Curve= 0 ,0
Exp/Cntr(USF)=0,0
Exp/Cntr=0.3,0.1

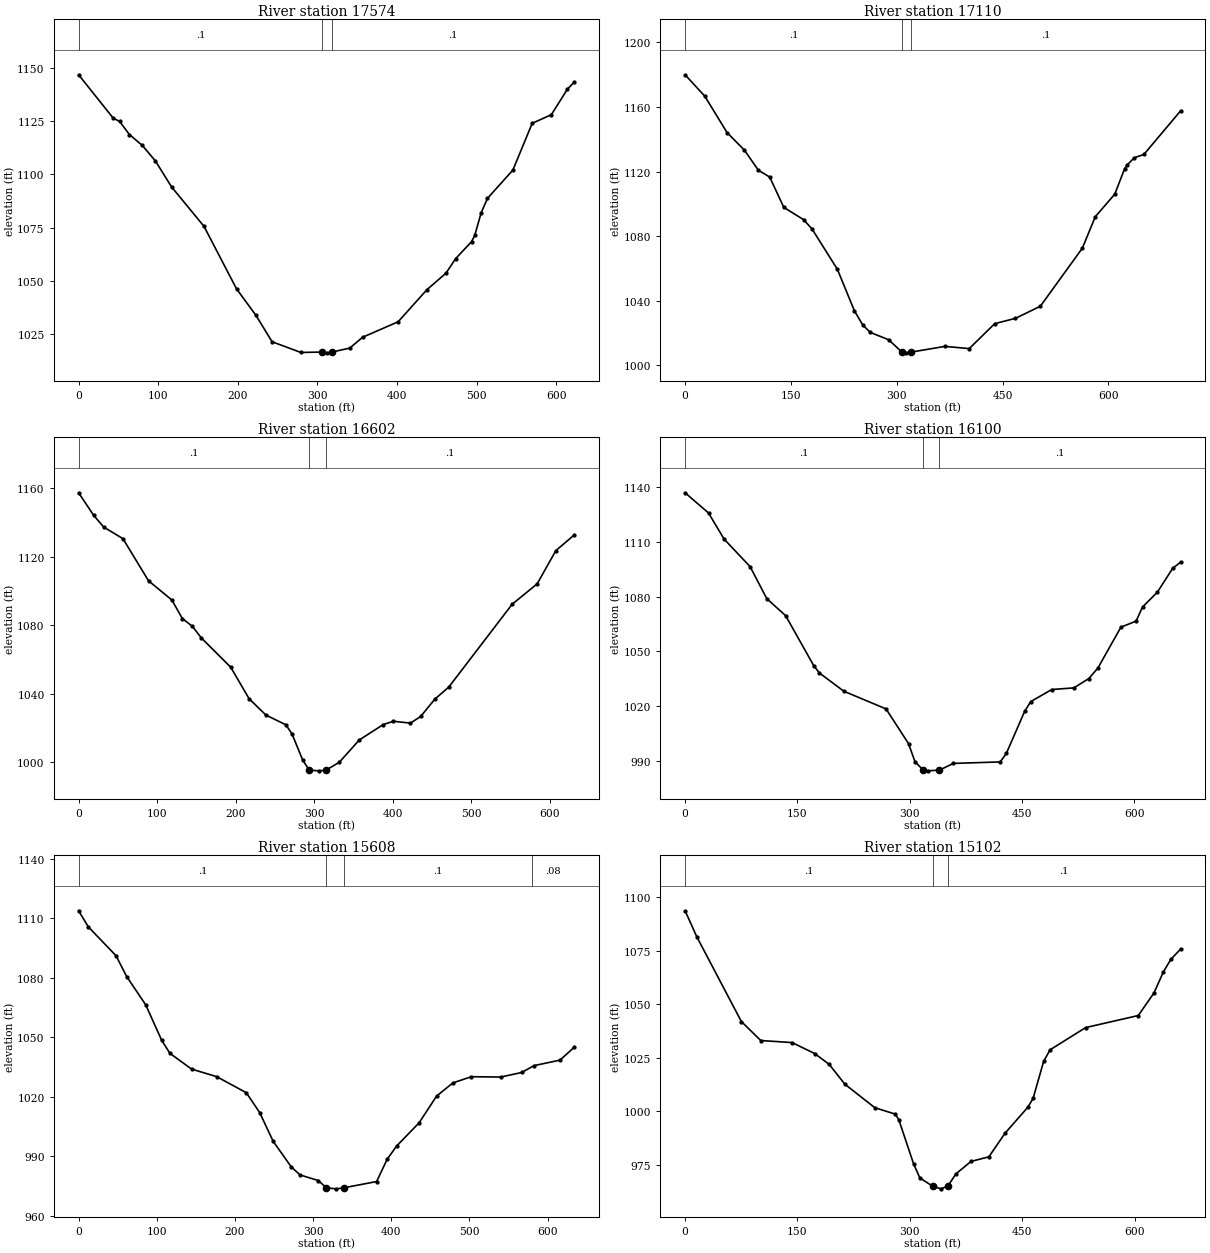
Type RM Length L Ch R = 1 ,17574   ,464.4,463.2,459.9
XS GIS Cut Line= 6
1598228.28274226  427334.00717851598179.54104184427585.621504679
1598162.30288734427684.1245885041598152.27337985427758.509282261
1598157.80256826427849.5202550891598166.82978117427948.930161253
#Sta/Elev= 30
       0 1146.64    43.4 1126.32    51.5 1124.75    63.8 1118.63    80.1 1113.49
    96.4 1106.25   116.8 1094.04   157.5 1075.57   198.3  1046.3   222.7 1033.87
     243 1021.48   279.1 1016.47  306.18 1016.66     312 1016.29  318.131016.655
   340.5 1018.51   356.7  1023.6   401.3 1030.85   437.4 1045.87   461.4 1053.65
   473.5 1060.43   493.6 1068.46   497.5  1071.3   505.5 1081.86   513.5 1088.71
   545.4 1101.95   569.7  1123.9   593.7 1127.91   613.9 1139.89   622.4 1143.19
#Mann= 3 ,-1,0
       0      .1       0  306.18    .045       0  318.13      .1       0
Bank Sta=306.18,318.13
XS Rating Curve= 0 ,0
Exp/Cntr(USF)=0,0
Exp/Cntr=0.3,0.1

Type RM Length L Ch R = 1 ,17110   ,513.3,508.8,499.1
XS GIS Cut Line= 6
1597736.60918492427368.5979885911597736.60918492427624.848132253
1597755.77942218427730.3302047551597809.93285717427826.925812095
1597865.88025184427927.6641276781597922.67639808428025.145560011
#Sta/Elev= 30
       0  1179.9    27.9 1166.65    59.4 1144.16    83.9 1133.31   103.9 1120.82
   119.9 1116.58   139.9 1097.83   167.9 1090.22   179.9 1084.45   215.9 1059.42
   239.9 1033.82   251.9 1024.95   262.4 1020.45   288.5 1015.86   307.2 1008.27
   312.9 1007.77  320.681008.256   368.3 1011.76   402.7 1010.39   438.8 1025.83
   468.2 1029.13   503.5 1036.62     563 1072.57   581.3 1092.01     609 1106.03
   622.8 1121.64   626.8  1124.2   636.7 1128.57   650.2 1130.57   702.3 1157.61
#Mann= 3 ,-1,0
       0      .1       0   307.2    .045       0  320.68      .1       0
Bank Sta=307.2,320.68
XS Rating Curve= 0 ,0
Exp/Cntr(USF)=0,0
Exp/Cntr=0.3,0.1

Type RM Length L Ch R = 1 ,16602   ,478.4,501.7,512.9
XS GIS Cut Line= 6
1597219.72373575427912.1438174991597301.71012034427961.153562009
1597548.56100459428050.4345514181597618.62484084428079.737970501
1597703.26181068428121.9173480871597793.71208909428170.438904583
#Sta/Elev= 30
       0 1157.23    19.1  1144.1      32  1137.2    56.4 1130.46      89 1105.87
   118.8 1094.62   132.1 1083.82   144.9 1079.29   156.2 1072.56   193.7 1055.42
   217.2 1036.98   238.5  1027.5     264 1021.78   271.8 1016.49   285.3 1001.32
   293.7   995.3   306.5  994.92     315  995.29     332  999.91   357.5 1012.94
   387.9 1021.91   400.9 1023.86   422.6 1022.78   435.7 1026.64   453.5 1036.68
   471.5 1043.82   552.2 1092.17     584 1104.04   607.9 1123.49   631.2 1132.57
#Mann= 3 ,-1,0
       0      .1       0   293.7    .045       0     315      .1       0
Bank Sta=293.7,315
XS Rating Curve= 0 ,0
Exp/Cntr(USF)=0,0
Exp/Cntr=0.3,0.1

Type RM Length L Ch R = 1 ,16100   ,507,491.9,479
XS GIS Cut Line= 6
1597187.19853833427959.3120302561597236.65906934428055.489987507
1597264.48217642428149.4458363351597186.81140001428393.605781093
 1597186.5495895428488.3496860861597204.24148326  428591.1936405
#Sta/Elev= 30
       0 1136.92    31.3 1125.84    52.1 1111.51    86.8 1096.43   109.2  1078.8
   134.3 1069.51   171.8 1042.13   179.4 1038.06     212 1028.05   268.5 1018.32
   298.6  999.23   307.1  989.41   318.2  984.75   324.3  984.35   339.9  984.75
   358.4  988.43   421.1  989.24   429.2  993.92   453.8  1017.1   461.9 1022.37
   489.9 1028.97   519.4 1029.86   539.5    1035   551.5 1040.73   582.3 1063.19
   602.6  1066.5   611.2 1074.27     631 1082.36   651.3 1095.38   662.1 1098.88
#Mann= 3 ,-1,0
       0      .1       0   318.2    .045       0   339.9      .1       0
Bank Sta=318.2,339.9
XS Rating Curve= 0 ,0
Exp/Cntr(USF)=0,0
Exp/Cntr=0.3,0.1

Type RM Length L Ch R = 1 ,15608   ,495.2,505.8,515.4
XS GIS Cut Line= 6
1596656.89087193428262.9118167611596752.59343642428430.429526344
1596797.71244067428499.5750573431596881.04363884428558.689112335
1597024.29466468428635.2601534281597103.26005793428686.197715595
#Sta/Elev= 30
       0 1113.85    12.4 1105.73    47.8  1091.2    61.6 1080.58    85.8 1066.42
   106.3 1048.47   116.8 1041.91   144.5 1033.95   176.6 1030.14   214.6 1022.02
   231.7 1011.97     249  997.46   272.1  984.58   283.3  980.54   306.6   977.7
  317.13974.0254   329.5  973.51  339.25 974.035   381.3  977.19   394.8  988.44
     407  995.17   435.6 1006.79   458.1 1020.34   478.8 1026.96   502.5  1030.1
   540.1 1029.93   566.9 1032.23   582.7  1035.7     616 1038.47   634.1 1044.96
#Mann= 4 ,-1,0
       0      .1       0  317.13    .045       0  339.25      .1       0
   580.1     .08       0
Bank Sta=317.13,339.25
XS Rating Curve= 0 ,0
Exp/Cntr(USF)=0,0
Exp/Cntr=0.3,0.1

Type RM Length L Ch R = 1 ,15102   ,515.8,500.3,482.8
XS GIS Cut Line= 6
1596377.43014476428450.7346038371596444.50514184428646.150879666
1596449.30992226428728.1910699161596441.11144784428903.002072006
1596475.44175975428989.2571488321596537.81761926429073.110327587
#Sta/Elev= 30
       0  1093.7    15.8 1081.42    75.1 1041.94     101 1033.08   142.8 1032.11
   172.9    1027   192.3 1021.95   213.3 1012.64   253.3 1001.67   280.7  998.67
   285.4  995.92     305   975.4   313.4  968.83   330.4  965.03   341.5  963.77
  350.55  965.04   361.5  970.76   381.5  976.56   405.5  978.75     427  989.75
   457.6 1001.96   464.5 1006.05   478.6 1023.39   487.2 1028.75   534.6 1039.12
   604.9 1044.76   625.8  1055.3   638.4 1065.17   648.3 1070.97   661.4 1075.84
#Mann= 3 ,-1,0
       0      .1       0   330.4    .045       0  350.55      .1       0
Bank Sta=330.4,350.55
XS Rating Curve= 0 ,0
Exp/Cntr(USF)=0,0
Exp/Cntr=0.3,0.1

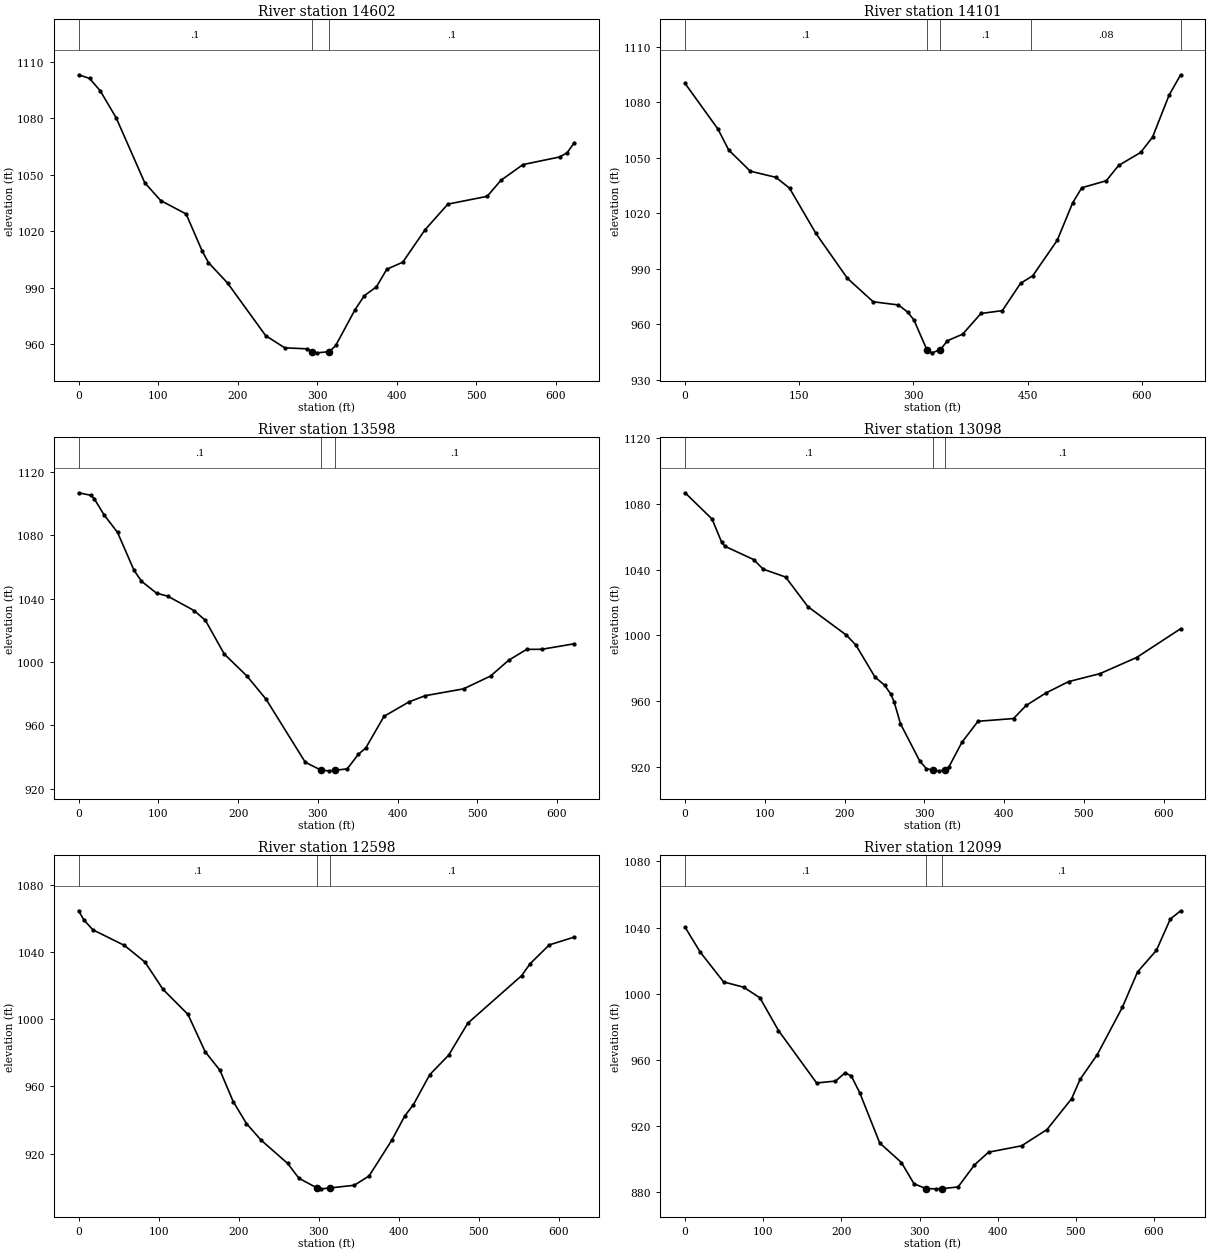
Type RM Length L Ch R = 1 ,14602   ,496.1,500.8,495.7
XS GIS Cut Line= 6
1595905.00392425429027.1875191781596087.37134168429026.502481177
1596162.47880301429028.1924384241596337.31211476429035.845638335
1596423.54192917429055.6789320111596511.86786801429106.321219176
#Sta/Elev= 30
       0 1103.22    13.7 1101.31    27.1 1094.72    47.1 1080.38    83.1 1045.76
   103.1  1036.3   135.1 1029.13   155.1 1009.58   163.1  1003.3   187.1  992.41
   235.1  964.36   259.1  957.88   287.2  957.37  292.86 955.858   299.2  955.23
   315.2  955.84   323.2  959.19   347.4  978.21   359.2  985.69   374.3  990.37
   387.3  999.73   407.3 1003.45   435.4 1020.74   464.1 1034.39   513.4 1038.51
   530.7 1047.03   558.5 1055.43   604.6 1059.48   613.9 1061.68   622.8 1066.99
#Mann= 3 ,-1,0
       0      .1       0  292.86    .045       0   315.2      .1       0
Bank Sta=292.86,315.2
XS Rating Curve= 0 ,0
Exp/Cntr(USF)=0,0
Exp/Cntr=0.3,0.1

Type RM Length L Ch R = 1 ,14101   ,495,502.6,505.9
XS GIS Cut Line= 6
1595794.39587776 429349.299407751595872.82518284429420.303530842
1595954.92180343429474.775862843 1596032.4770945429496.222342253
 1596208.1719531429490.7991247621596396.43666843429517.638309926
#Sta/Elev= 30
       0 1090.06    43.2 1065.41    57.3 1054.11    85.6 1042.68   119.3 1039.35
   137.2  1033.5   171.8 1009.08   213.2  984.81   247.1  972.11   280.3  970.38
   292.4  966.55   300.5  962.39   317.6  946.27   324.5  944.51  335.47946.2281
   344.6  951.03   364.7  954.61   388.7  965.78   416.8  967.31   440.8  982.09
   456.8  986.15     489 1005.35   509.2 1025.54   521.2 1033.72   553.4  1037.5
   569.6 1045.76   598.5 1052.77   614.2 1061.05   635.9 1083.73   651.1 1094.76
#Mann= 5 ,-1,0
       0      .1       0   317.6    .045       0  335.47      .1       0
  454.79     .08       0  651.06      .1       0
Bank Sta=317.6,335.47
XS Rating Curve= 0 ,0
Exp/Cntr(USF)=0,0
Exp/Cntr=0.3,0.1

Type RM Length L Ch R = 1 ,13598   ,504,500.7,493
XS GIS Cut Line= 6
1595477.24854617429588.1138907521595694.57652359429723.773068249
1595780.75942209429774.4947515881595841.91317117 429818.50778693
1595903.46226068429886.0207752591595965.70163751 429962.45828642
#Sta/Elev= 30
       0  1106.9    15.9 1105.25    19.8 1102.97    31.7 1093.09    48.8 1081.85
    69.4 1057.99    78.8 1051.02    97.7 1043.45   111.8 1041.56   144.8 1032.45
     159  1026.3   182.6 1005.02   210.9  991.19     235   976.5   284.2  936.63
   304.4  931.52   313.7  931.18  321.08931.5154   336.9  932.42   350.8  941.63
   360.1   945.6     383  965.61   414.5  974.79   434.5  978.65   482.7  982.98
   516.6  991.08   539.4 1001.08   561.9 1007.94   580.9    1008   621.5 1011.46
#Mann= 3 ,-1,0
       0      .1       0   304.4    .045       0  321.08      .1       0
Bank Sta=304.4,321.08
XS Rating Curve= 0 ,0
Exp/Cntr(USF)=0,0
Exp/Cntr=0.3,0.1

Type RM Length L Ch R = 1 ,13098   ,492.9,499.4,507.9
XS GIS Cut Line= 6
1595266.44516201430197.0808486791595362.98761985430204.187461749
1595453.83520718430209.5788551721595531.23236209430209.916452929
1595630.06418543430194.6323627531595882.60403468430151.511714086
#Sta/Elev= 30
       0 1086.73    33.8 1070.75    45.8 1056.67    49.8 1054.18    85.9 1046.08
    97.9 1040.22     126 1035.43     154 1017.38   202.1 1000.11   214.1  994.07
   238.1  974.53   250.1  969.61   258.1  964.03   262.1  959.47   270.1  946.06
   294.4  923.25   302.5  918.81   310.6  917.82   318.7  917.42  326.14917.8196
   330.9  919.87   347.1  934.78   367.3  947.59   411.9  949.27   427.7  957.22
   452.5  964.84   480.9  971.75   520.3  976.61   566.1  986.41   621.4 1003.95
#Mann= 3 ,-1,0
       0      .1       0   310.6    .045       0  326.14      .1       0
Bank Sta=310.6,326.14
XS Rating Curve= 0 ,0
Exp/Cntr(USF)=0,0
Exp/Cntr=0.3,0.1

Type RM Length L Ch R = 1 ,12598   ,495.1,499.3,508.3
XS GIS Cut Line= 6
1595155.28068617430388.3088126781595331.51556993430574.334359258
1595400.29102293430646.928374171 1595451.1318005430702.075901672
1595510.95976484430767.727345169  1595585.432713430833.024130583
#Sta/Elev= 30
       0 1064.57     6.4 1059.22    17.7 1053.27    57.3 1043.91      83 1033.98
   105.4 1017.78   136.6 1002.86   158.2  980.55   176.6  969.56   193.1  950.98
   209.7  937.86     228  927.97   261.1  914.15   275.2   905.3   297.8  899.54
   297.8  899.53   303.4     899  314.46899.5508   344.4  901.13   362.9  906.68
   391.1  927.86   407.4  942.33   418.3  949.17   438.7     967   462.4  978.68
   486.2  997.64   553.5 1025.97     564 1033.03     588 1044.25   619.1 1048.89
#Mann= 3 ,-1,0
       0      .1       0   297.8    .045       0  314.46      .1       0
Bank Sta=297.8,314.46
XS Rating Curve= 0 ,0
Exp/Cntr(USF)=0,0
Exp/Cntr=0.3,0.1

Type RM Length L Ch R = 1 ,12099   ,510,503,485.6
XS GIS Cut Line= 6
1594973.44738843430606.0272092521595005.35053983430696.262921169
1595032.15855709430957.4005222621595061.16702926   431029.737976
1595111.47434334431110.2148491741595171.88367134431193.725180835
#Sta/Elev= 30
       0 1040.14    19.4 1025.11    49.3 1007.13    74.8 1003.97    95.7  997.58
   119.5  977.78   168.3  946.12   192.4  947.26   204.5  952.12   212.5  950.49
   223.4  940.27   249.1  909.85   276.8  898.08   292.9  885.25  308.27882.3122
   320.8  882.18   329.2   882.3   349.3  883.32   370.2  896.59   388.3  904.31
   430.6  908.17   463.1  917.99   494.6   936.6   505.5  948.34   527.4  963.22
   559.5  991.81     579 1013.19   603.1 1026.22   620.9 1045.12   634.1 1050.11
#Mann= 3 ,-1,0
       0      .1       0  308.27    .045       0   329.2      .1       0
Bank Sta=308.27,329.2
XS Rating Curve= 0 ,0
Exp/Cntr(USF)=0,0
Exp/Cntr=0.3,0.1

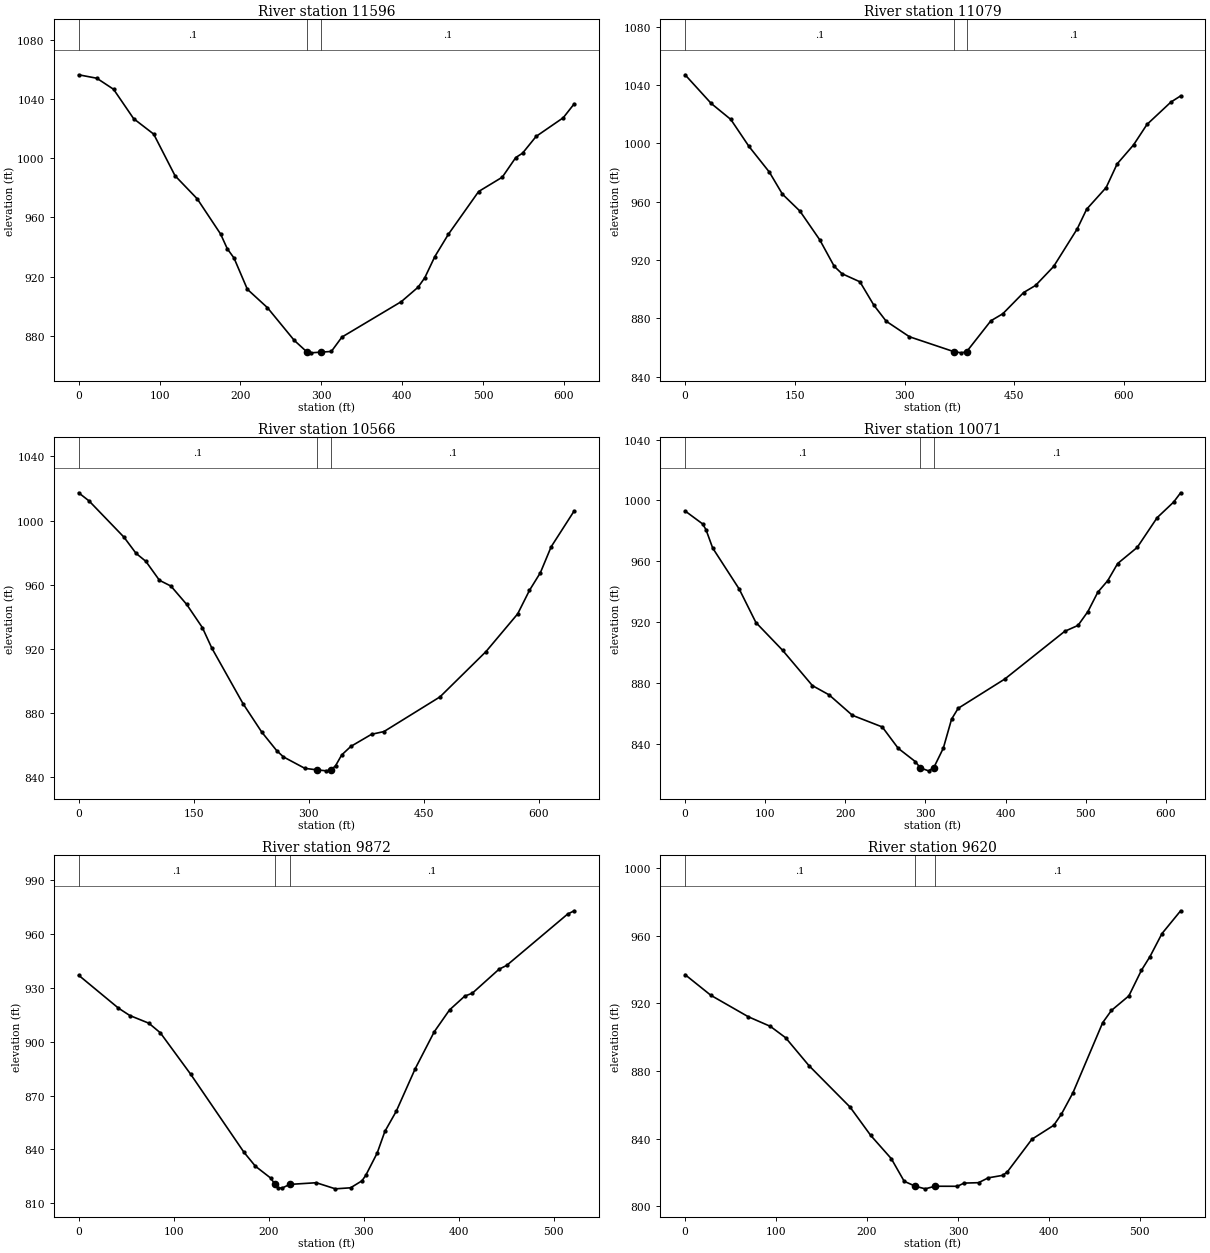
Type RM Length L Ch R = 1 ,11596   ,506,517.4,527.8
XS GIS Cut Line= 6
1594478.38407409431240.5659664271594653.64159758431286.788314924
1594822.85516992431331.4165064991594895.37536609431350.543108672
1594979.44343942431374.9003434181595068.98328659431403.019053593
#Sta/Elev= 30
       0 1056.26    22.5 1053.92    43.2 1046.47      68 1026.65    92.8 1016.22
   119.2  988.11   146.6  972.56   175.5   948.8   183.8  938.83   192.1  932.59
   208.6   911.5   233.4   899.1   266.5  877.06   282.4  869.14   287.2  868.62
   299.6   869.1   312.4  869.55   325.5  879.26   398.9  903.17   419.6  912.89
   427.9  919.26   440.3  933.53     457  948.56   494.5  977.49   523.7  987.15
   540.4 1000.41   548.8 1003.37   565.6 1014.69   599.1 1027.27   612.6 1036.63
#Mann= 3 ,-1,0
       0      .1       0   282.4    .045       0   299.6      .1       0
Bank Sta=282.4,299.6
XS Rating Curve= 0 ,0
Exp/Cntr(USF)=0,0
Exp/Cntr=0.3,0.1

Type RM Length L Ch R = 1 ,11079   ,509.4,512.6,511.3
XS GIS Cut Line= 6
1594426.57971576 431500.288216011594596.79984775431631.889986917
1594655.78988726 431701.623771341594662.44013642431801.937875167
1594676.85316534431876.9856253421594767.50193417432048.034167752
#Sta/Elev= 30
       0 1047.12    35.7 1027.45    62.5 1016.48    87.3  997.99   115.2  980.37
     133  965.29     157  953.63   184.1  933.91   203.9  915.74   214.4  910.73
     239  905.15   258.1  889.07   274.9  878.12   306.7  867.47  367.36857.2614
   377.7  856.44   384.9  857.27     418  878.42   434.3  883.24   462.8  897.81
   479.1  902.67   503.8  915.67   536.1  941.51   548.9  954.93   575.6  969.81
   590.6     986     613  999.01   631.4 1013.07   664.1  1028.4   677.4 1032.64
#Mann= 3 ,-1,0
       0      .1       0  367.36    .045       0   384.9      .1       0
Bank Sta=367.36,384.9
XS Rating Curve= 0 ,0
Exp/Cntr(USF)=0,0
Exp/Cntr=0.3,0.1

Type RM Length L Ch R = 1 ,10566   ,506.8,495.3,483
XS GIS Cut Line= 6
1594218.31733701431683.3610125931594272.76575041431935.746528593
1594270.24708007432032.427317747 1594307.8785096432107.434967592
1594367.57983376432186.9850053341594439.43959817432267.519293085
#Sta/Elev= 30
       0 1017.31    13.6 1012.23    59.1  989.66    74.9  979.54    87.6  974.61
   105.4  962.75   120.4  959.14   140.9  947.73   161.4  933.25   173.7   920.5
   214.4  885.84   238.8  868.14   258.4  856.51   267.1  852.65   295.1   845.5
   311.1  844.56   323.1  843.96  329.21844.5493   335.1  847.15   343.1  853.87
     355  859.18     382  866.74   398.2  868.44   471.3  890.07   531.3  918.32
   572.6  941.81     588  956.48   602.2  967.46   616.3  983.65   646.3 1005.99
#Mann= 3 ,-1,0
       0      .1       0   311.1    .045       0  329.21      .1       0
Bank Sta=311.1,329.21
XS Rating Curve= 0 ,0
Exp/Cntr(USF)=0,0
Exp/Cntr=0.3,0.1

Type RM Length L Ch R = 1 ,10071   ,200.3,199.1,196.1
XS GIS Cut Line= 6
1593767.01115301432314.3154593411594014.15075059432383.002329841
1594111.34806275432406.5649467561594183.86530617432428.425139248
 1594270.9766805432450.9493724261594364.52767451 432473.43489176
#Sta/Elev= 30
       0   993.1    21.9  984.59    26.1  980.79    34.4  968.79    67.6  941.76
    88.4  919.82   121.6  901.65   158.9   878.4   179.7  872.33   208.8  858.89
   246.1  851.24     266  837.21   287.3  828.52  293.58824.3638   303.8  822.42
  310.29824.4103   322.3  837.32   332.6  856.38   340.8  863.47   399.1  882.75
   473.8  914.05   490.4  917.93   502.8  927.07   515.1  939.72   527.5  947.34
   539.9  958.59   564.3  969.16   589.2  988.72   609.8  998.96   618.5 1005.05
#Mann= 3 ,-1,0
       0      .1       0  293.58    .045       0  310.29      .1       0
Bank Sta=293.58,310.29
XS Rating Curve= 0 ,0
Exp/Cntr(USF)=0,0
Exp/Cntr=0.3,0.1

Type RM Length L Ch R = 1 ,9872    ,242.4,252.1,258.3
XS GIS Cut Line= 2
1593806.29262087432595.7892879781594327.15944907432565.843982525
#Sta/Elev= 30
       0  936.95    41.9  918.64    53.9  914.52    73.9  910.25      86  904.91
     118  881.82   174.1  838.39   186.1  830.66   202.2  824.06   206.8 820.518
   210.2  818.58   214.2   818.5   222.2  820.54   250.2  821.47   270.3  818.07
   286.3  818.65   298.3  822.54   302.3  825.59   314.3  837.98   322.4  850.02
   334.4  861.25   354.4  884.98   374.4  905.48   390.5  917.65   406.5  925.32
   414.5  926.95   442.6  940.29   450.6  942.39   514.7  970.93   521.7  972.81
#Mann= 3 ,-1,0
       0      .1       0   206.8    .045       0   222.2      .1       0
Bank Sta=206.8,222.2
XS Rating Curve= 0 ,0
Exp/Cntr(USF)=0,0
Exp/Cntr=0.3,0.1

Type RM Length L Ch R = 1 ,9620    ,251.1,253,252.8
XS GIS Cut Line= 2
1593794.09128248432642.5633122361594202.76571444433002.842087783
#Sta/Elev= 30
       0  937.04    28.3  924.83    69.5  912.12    93.7  906.44   110.5   899.7
   136.1  883.23   181.4  858.62     204  841.91   226.7   828.1   240.9  814.69
   253.3  811.76     264  810.24   274.7  811.78   299.4  811.75   306.6  813.64
   322.6  813.88   333.3  816.75   349.3  818.24   354.3  820.31   381.3  839.61
   405.3  847.86   413.8  854.53   426.4  867.11   459.1  908.62   468.7  915.85
   487.9  924.49   501.6  939.54   511.1  947.75   524.3  961.37   544.8  974.86
#Mann= 3 ,-1,0
       0      .1       0   253.3    .045       0   274.7      .1       0
Bank Sta=253.3,274.7
XS Rating Curve= 0 ,0
Exp/Cntr(USF)=0,0
Exp/Cntr=0.3,0.1

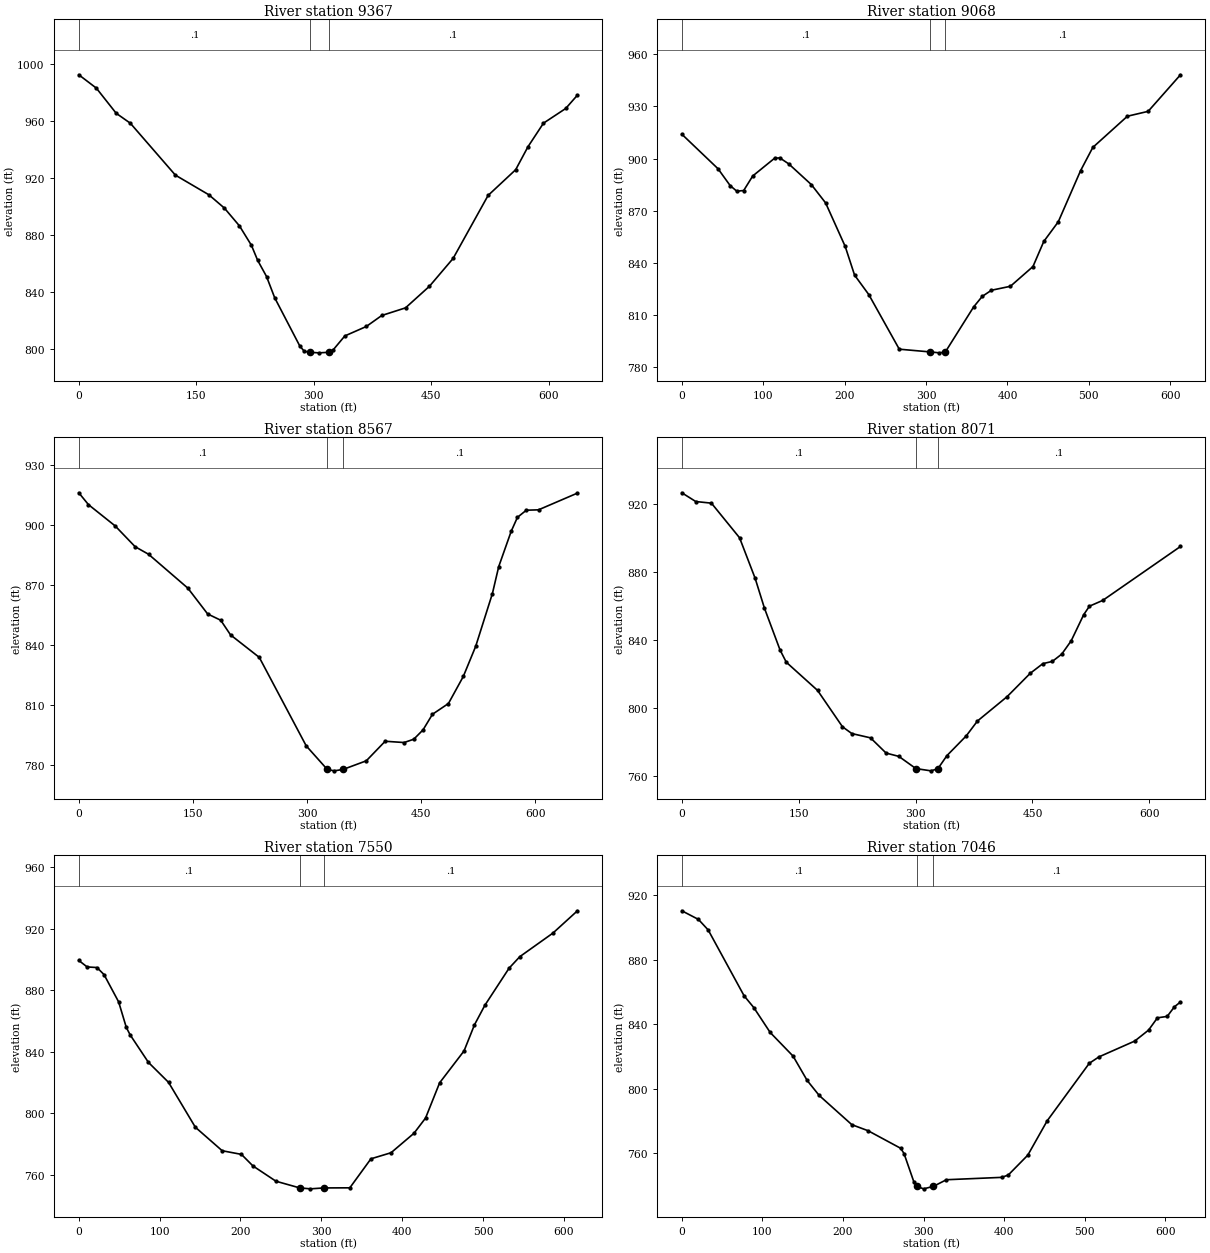
Type RM Length L Ch R = 1 ,9367    ,298.8,298.6,298.1
XS GIS Cut Line= 6
1593555.89327219432761.7893599431593647.01612145432820.397182361
1593721.82863587432881.8439098611593772.48831145432937.604625107
1593841.49473511 433009.992603691594026.95597836433186.978470192
#Sta/Elev= 30
       0  992.37    22.4     983    47.8   965.3    65.8  958.35   123.4  921.85
   166.1  908.06     186  898.68   205.2  886.19   220.5  872.54   228.5  861.93
   239.8  850.62   250.2   835.7   282.3  801.77     288  798.09   295.6  797.34
   306.6  796.99   319.1  797.35   324.7  798.95   339.8  808.87   367.2   815.5
     387  823.24   417.3  828.59   447.9  843.79   478.1  863.33   522.8  907.61
     558  925.67   573.7   941.8   593.5  958.37   621.9  968.68   636.9  978.08
#Mann= 3 ,-1,0
       0      .1       0   295.6    .045       0   319.1      .1       0
Bank Sta=295.6,319.1
XS Rating Curve= 0 ,0
Exp/Cntr(USF)=0,0
Exp/Cntr=0.3,0.1

Type RM Length L Ch R = 1 ,9068    ,510,500.6,489.9
XS GIS Cut Line= 6
1593345.20031685432941.7731939261593476.13214159433067.106276587
1593602.54888351433188.1178455951593657.23381351433239.451076254
1593721.44726776433298.906994089 1593790.4248201433362.424255505
#Sta/Elev= 30
       0     914    44.5  894.13    59.4  884.44    67.6  881.22      76  881.63
    87.1  889.98   113.9  900.16   120.3  900.39   131.3  896.95   159.1  885.03
   176.6  874.52   200.7  849.46   212.2  832.99   229.6  821.85   267.1  790.43
  305.33788.8438   316.4  788.33   323.7  788.84   358.4  814.69     369  820.77
   380.3   824.3   403.6  826.58   431.3  837.92   444.6  852.35   462.4  863.64
   489.7  892.95   504.8  906.39   547.3  924.33   572.8  927.13   612.5  948.15
#Mann= 3 ,-1,0
       0      .1       0  305.33    .045       0   323.7      .1       0
Bank Sta=305.33,323.7
XS Rating Curve= 0 ,0
Exp/Cntr(USF)=0,0
Exp/Cntr=0.3,0.1

Type RM Length L Ch R = 1 ,8567    ,499.1,496.5,493.4
XS GIS Cut Line= 6
1593076.51220593433495.4669684171593174.00085609433539.375673249
1593270.99344426433577.7046648411593355.67240876433600.863411173
1593609.19224292433532.7759489271593701.85938042 433516.20774059
#Sta/Elev= 30
       0  916.19    12.7  910.27    47.8  899.64    74.1  889.24    91.7  885.48
   143.4  868.54   169.4  855.65   186.6  852.51   199.5  845.19   237.3  833.95
     299  789.74  326.68777.9662   335.7  777.26  347.25 777.932     378  782.27
   402.8  792.04   427.7   791.4   440.4  793.06   452.6  797.73     465  805.53
     486   810.9   505.5   824.4   521.8  839.45   543.8  865.86   552.1  879.32
   568.5  896.96   576.7  903.92   588.4  907.48   604.4  907.67   655.6  916.03
#Mann= 3 ,-1,0
       0      .1       0  326.68    .045       0  347.25      .1       0
Bank Sta=326.68,347.25
XS Rating Curve= 0 ,0
Exp/Cntr(USF)=0,0
Exp/Cntr=0.3,0.1

Type RM Length L Ch R = 1 ,8071    ,519.8,521,510.4
XS GIS Cut Line= 6
1592894.22287235433965.1874856651593084.48135009433976.055246085
 1593161.4359206433975.0552480821593331.45198476433933.587811336
1593424.55580117433945.5582598451593522.95094559433977.852158502
#Sta/Elev= 30
       0  926.72    17.9  921.57      38  920.61    74.1  900.25    94.1  876.39
   106.1  858.74   126.1  834.17   134.1  826.99   174.2  810.42   206.2     789
   218.2  785.01   242.2  782.48   262.2  773.52   278.5  771.58   300.4   764.4
   319.7  763.07  328.58764.2987   340.3  772.05     365  783.62   379.4  792.38
   417.5  806.74   447.2  820.48   463.4  826.17   475.5  827.46   487.6  831.76
   499.7  839.57   515.8  854.99   523.2  859.99   540.2  863.37     640  895.12
#Mann= 3 ,-1,0
       0      .1       0   300.4    .045       0  328.58      .1       0
Bank Sta=300.4,328.58
XS Rating Curve= 0 ,0
Exp/Cntr(USF)=0,0
Exp/Cntr=0.3,0.1

Type RM Length L Ch R = 1 ,7550    ,497.7,503.8,509.4
XS GIS Cut Line= 6
1592962.55770943434594.0707423391593041.57264325434543.615462676
  1593115.319543434496.524021417 1593326.0258145434361.977046415
1593408.74546534434328.9367581751593500.76890334434299.558208004
#Sta/Elev= 30
       0  899.45    10.3  895.22    22.5  894.82    31.2  890.25    49.3  872.47
    58.8  855.82    63.5  851.03    86.2  833.06     111  820.12   144.2  790.88
   177.4  775.58   201.2  773.21   215.4  765.71   243.9  755.74  273.43 751.367
   286.6  750.78  303.06751.3703   335.3  751.44   361.4  770.32   386.3  774.28
   414.7  786.97     429  796.87   446.4  819.79   476.6  840.55   489.5  857.54
   502.4  870.29   532.3  894.39   545.6  901.91   586.6  917.27   616.9  931.77
#Mann= 3 ,-1,0
       0      .1       0  273.43    .045       0  303.06      .1       0
Bank Sta=273.43,303.06
XS Rating Curve= 0 ,0
Exp/Cntr(USF)=0,0
Exp/Cntr=0.3,0.1

Type RM Length L Ch R = 1 ,7046    ,508.4,516.3,518.9
XS GIS Cut Line= 6
1593003.80106525434950.4378117621593096.37338668434935.625177339
1593355.57693651434894.1538035871593429.95900559434884.330660507
1593519.42175317434877.202393919 1593616.5016115434864.476697594
#Sta/Elev= 30
       0  910.36    20.6  905.01    32.7  898.48    77.3  857.62    89.4  850.27
   109.7  834.86   138.1   820.2   155.6  805.09   170.5  795.81     211  777.68
   231.2  773.92   271.7  763.01   275.8  759.75   287.9  742.34  291.58739.4499
   300.1  737.88   312.2   739.4   328.4  743.53   397.1     745   405.2  746.47
   429.4  758.77   453.5  780.11   505.7  815.75   517.7  819.73   562.1  829.54
   579.3  836.35   590.3  843.96   602.4  844.84   611.4  850.81   618.9  853.79
#Mann= 3 ,-1,0
       0      .1       0  291.58    .045       0   312.2      .1       0
Bank Sta=291.58,312.2
XS Rating Curve= 0 ,0
Exp/Cntr(USF)=0,0
Exp/Cntr=0.3,0.1