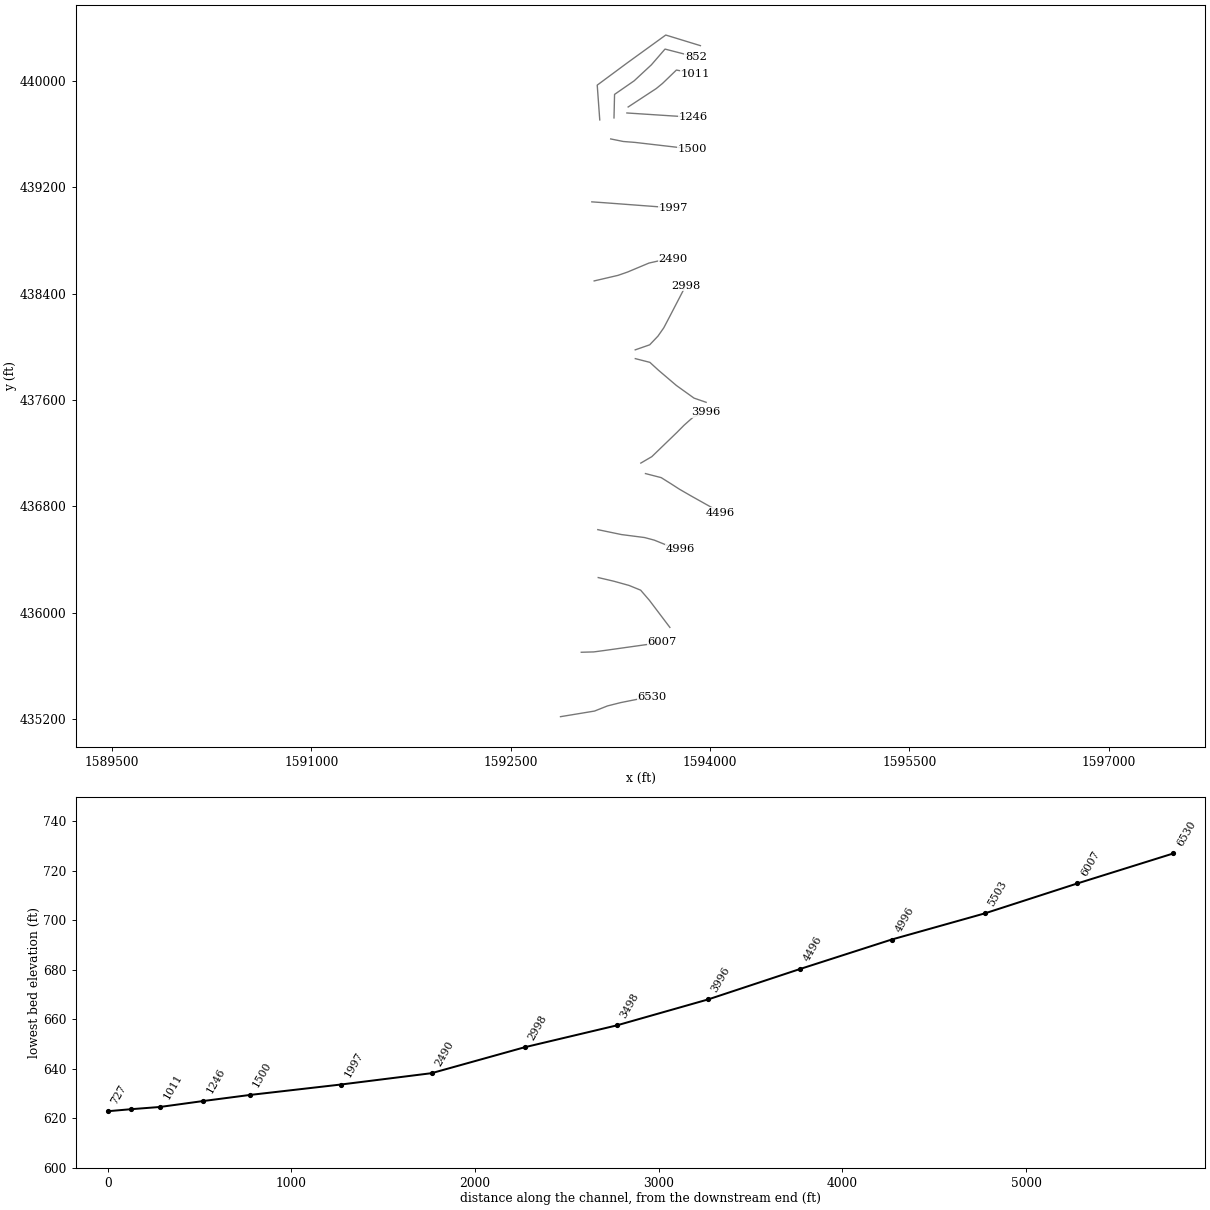
HEC-RAS study HAYNESRN.prj: HAYNESRN

--- HAYNESRN.g01 (geometry) --- (continued)

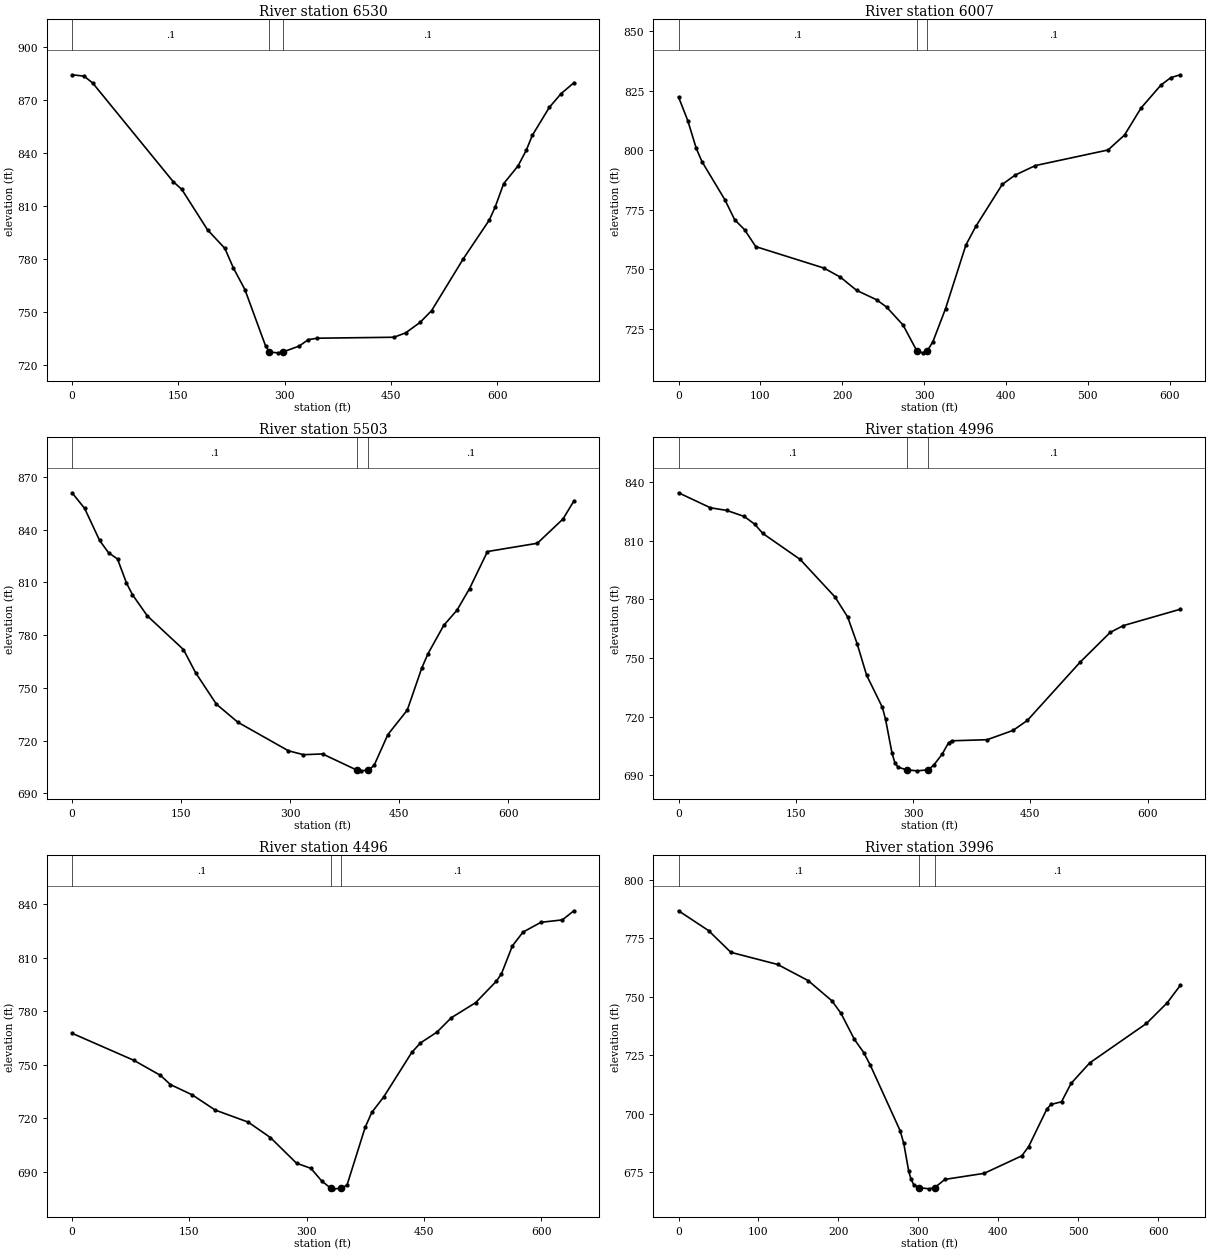
Type RM Length L Ch R = 1 ,6530    ,524.8,522.8,517.4
XS GIS Cut Line= 6
1592875.32855317435218.1147698461593131.48027185  435260.4047115
1593228.62968384435298.9679545911593328.93525751  435324.2392295
1593447.25326234435347.8402321791593566.01385158435366.191573426
#Sta/Elev= 30
       0  884.52      17  883.75    29.2  879.81   142.7  824.02   154.9  819.61
   191.3  796.66   215.7  786.19   227.8  775.05     244  762.85   273.2  730.91
   278.7  727.46   290.4  727.02  297.24727.4558   320.6  730.85   333.5  734.49
   346.4  735.31   454.4  735.85   470.8  738.31   491.2  744.22   507.5  750.89
   552.4  780.35   589.1  802.28   597.2  809.49   609.3  822.86   629.6   832.9
   641.1  841.67   649.8  850.24   673.7  866.02   690.3  873.81   708.4  879.98
#Mann= 3 ,-1,0
       0      .1       0   278.7    .045       0  297.24      .1       0
Bank Sta=278.7,297.24
XS Rating Curve= 0 ,0
Exp/Cntr(USF)=0,0
Exp/Cntr=0.3,0.1

Type RM Length L Ch R = 1 ,6007    ,510.9,503.9,496.7
XS GIS Cut Line= 6
1593031.49392326435702.8611756711593125.79655617435705.470094338
1593212.52735384 435717.063247011593385.82851642435741.386361092
1593460.10067759435751.8102247571593639.59146035435777.002759665
#Sta/Elev= 30
       0  822.26    11.3  812.35    21.7  800.67    28.6  795.17    56.6  779.16
    68.6  770.76    80.7  766.56    94.3  759.48   177.4   750.5   197.6   746.7
   217.8  741.07     242  737.17   254.1  734.13   274.3  726.57  291.04715.7986
   298.6  714.89  303.97715.7823   310.7  719.48   326.2   733.4   351.1  760.14
   363.2  767.95   395.5  785.57   411.2  789.48     436  793.49   524.8  800.04
     545  806.34   565.1  817.65   589.4  827.28   601.5  830.42   613.1   831.6
#Mann= 3 ,-1,0
       0      .1       0  291.04    .045       0  303.97      .1       0
Bank Sta=291.04,303.97
XS Rating Curve= 0 ,0
Exp/Cntr(USF)=0,0
Exp/Cntr=0.3,0.1

Type RM Length L Ch R = 1 ,5503    ,503.3,507,510.2
XS GIS Cut Line= 6
1593159.29255217436264.8735030891593276.18405068436237.511025012
1593391.44858393436205.5058396761593478.37557542 436170.00722301
1593543.85051009436094.1458261761593698.39580467435889.744660169
#Sta/Elev= 30
       0  861.04    17.3  852.13    37.8  833.97    50.1  826.94    62.5  823.37
    74.8  809.68      83  803.07   103.5  790.97   153.2   771.8   169.8  758.68
   198.4  740.76   227.9  730.47   297.5   714.2   318.2  711.98   344.4  712.41
   391.3  703.26   397.5  702.79  407.58703.2749   415.3  705.86   434.2   723.4
   460.9  737.33   480.9  761.33   489.4  769.43     511  785.52   529.4  794.28
   546.5  806.46   571.2   827.6   639.8  832.31     675  846.09     690  856.34
#Mann= 3 ,-1,0
       0      .1       0   391.3    .045       0  407.58      .1       0
Bank Sta=391.3,407.58
XS Rating Curve= 0 ,0
Exp/Cntr(USF)=0,0
Exp/Cntr=0.3,0.1

Type RM Length L Ch R = 1 ,4996    ,510.5,500.6,493.7
XS GIS Cut Line= 6
1593155.98251942436625.4544748371593333.87127125436588.464391336
1593507.43227585436566.0697510841593580.75463575436546.658372596
1593668.46476218436511.0892180061593777.79361175436477.270059928
#Sta/Elev= 30
       0  834.65    40.8  826.97    61.8   825.6      84  822.52    97.4  818.56
   107.8  813.81   155.6  800.49   200.2  781.22   216.3     771   228.4  757.34
   240.5  741.22   260.7  724.71   264.7  718.66     273  701.29   276.8   696.2
   280.8  694.09  291.53692.7604     305  692.22   319.4  692.74   326.6  695.25
   337.3  700.87   345.3  706.61   349.4  707.61   394.7  708.17   427.8  712.94
     446  718.01   513.6   747.9     552  763.12   568.8  766.61   641.7     775
#Mann= 3 ,-1,0
       0      .1       0  291.53    .045       0   319.4      .1       0
Bank Sta=291.53,319.4
XS Rating Curve= 0 ,0
Exp/Cntr(USF)=0,0
Exp/Cntr=0.3,0.1

Type RM Length L Ch R = 1 ,4496    ,491.2,499.4,511.8
XS GIS Cut Line= 6
1593514.72163133437047.2954946761593632.93399334437016.880857334
1593707.42761075436970.1808195111593770.60169701436929.492580667
1593857.22061826436879.5048197511594080.80022359 436754.30001767
#Sta/Elev= 30
       0  767.64      79  752.45     113  743.99   125.8  738.82   153.6  733.06
     183  724.51   225.1  717.75   253.6  709.05   286.9  694.66   305.3  691.78
     319  684.72   330.9  680.53   333.1  680.27  344.28 680.529   351.5  682.46
   374.6  714.76   383.1  723.19   398.3  731.87   434.3  756.95   445.3   762.2
   466.4   768.3   484.7  776.35   515.8  784.82   542.3  796.87   548.9  801.11
   562.8  816.71   576.4  824.48   599.3  829.96   626.8  831.34   641.4  836.45
#Mann= 3 ,-1,0
       0      .1       0   330.9    .045       0  344.28      .1       0
Bank Sta=330.9,344.28
XS Rating Curve= 0 ,0
Exp/Cntr(USF)=0,0
Exp/Cntr=0.3,0.1

Type RM Length L Ch R = 1 ,3996    ,512.9,497.7,481.2
XS GIS Cut Line= 6
 1593479.6281976437126.3028825821593562.74712583437174.895633176
1593751.58959593437357.2272895131593804.75418776437410.841027424
1593871.65103559437470.3687954991593967.07046418437511.148897678
#Sta/Elev= 30
       0  786.75    37.6  778.27    65.4  769.01   123.9  763.83     162  756.96
   191.8  748.32   203.1     743     220  731.81   231.6  726.22   239.9  720.78
   277.2   692.8   281.7  687.39   287.9  675.56   290.8  672.09   294.4  669.63
   300.2  668.56   313.4     668  320.51 668.551   333.2  672.04   382.2  674.61
   429.4  682.11   437.9  686.05   460.5  701.95   465.6  704.02     479  705.18
     491  713.04   514.4  721.82   585.2  738.62   611.2  747.45   627.6  754.92
#Mann= 3 ,-1,0
       0      .1       0   300.2    .045       0  320.51      .1       0
Bank Sta=300.2,320.51
XS Rating Curve= 0 ,0
Exp/Cntr(USF)=0,0
Exp/Cntr=0.3,0.1

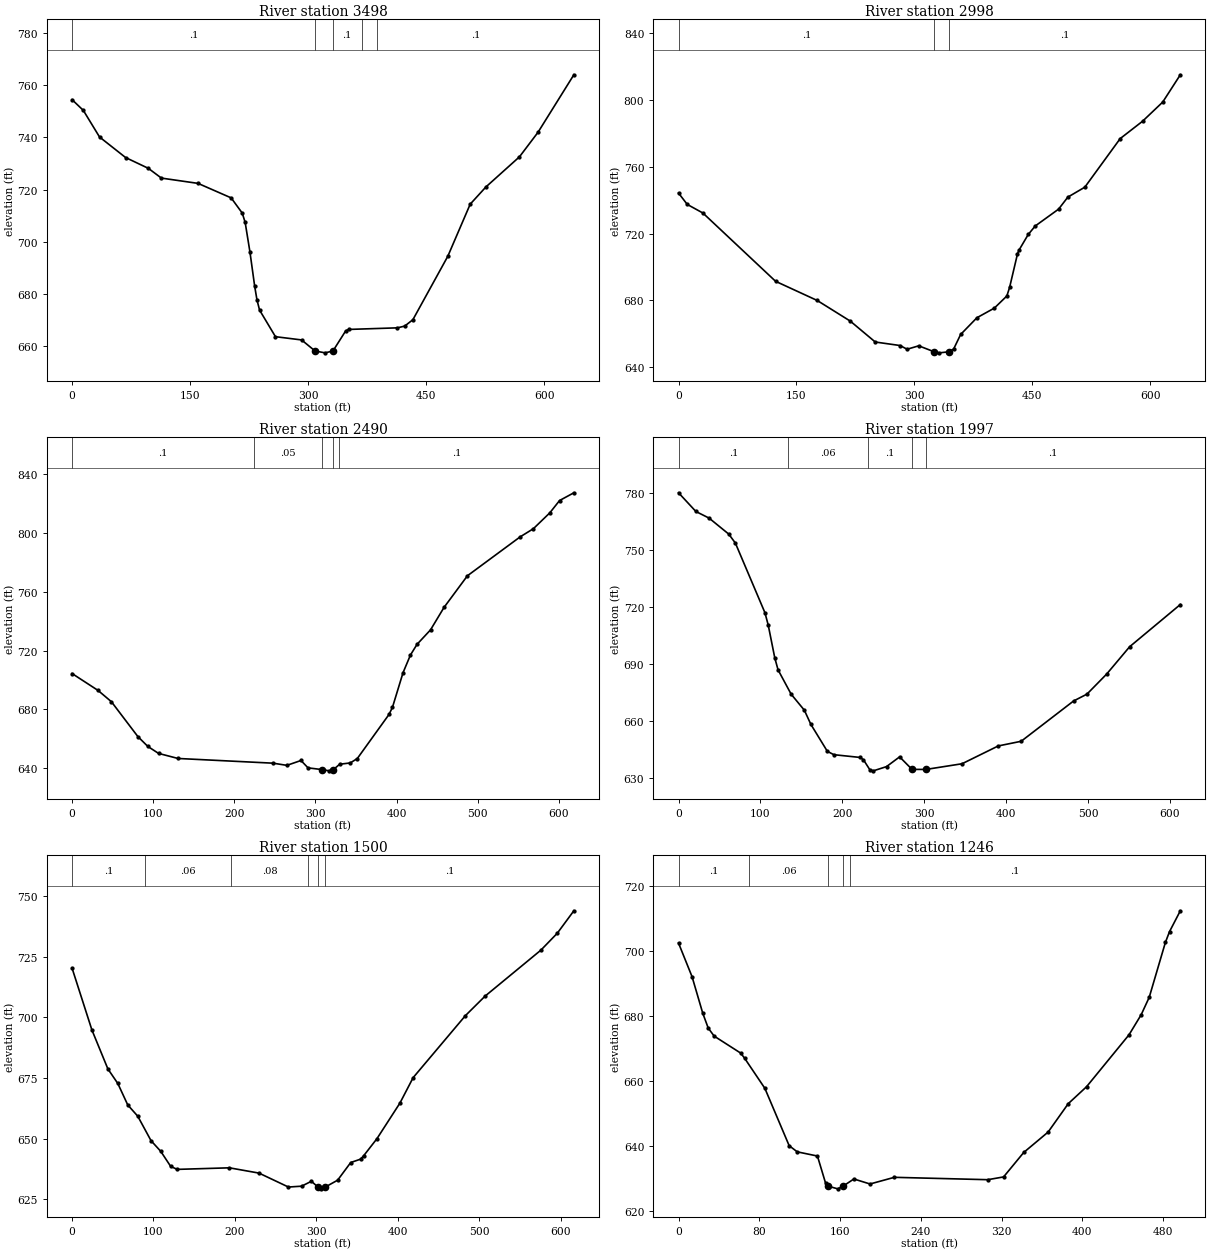
Type RM Length L Ch R = 1 ,3498    ,483.2,500.8,519.8
XS GIS Cut Line= 6
1593438.28379209437912.3357593421593547.80949168437884.255763009
1593613.45568584437824.1436785011593747.36650726 437710.18032375
1593879.83277775437615.2585975831593971.16100718437583.593634665
#Sta/Elev= 30
       0  754.41    14.3  750.31    34.9  740.12      68  732.26    96.9  728.13
   113.5  724.39     160  722.37   202.1  716.82   216.2     711   219.9  707.44
     226  696.08     232  682.98   234.9  677.79   238.2  673.87   258.4  663.68
   291.6  662.44   308.7  658.21   321.4   657.5   331.4  658.19   347.5  665.85
   351.2  666.46   413.3  667.07   422.6  667.74     433  670.19   477.3  694.43
   505.8  714.41   525.8  721.01   568.4  732.54     592  741.94   637.5  763.94
#Mann= 5 ,-1,0
       0      .1       0   308.7    .045       0   331.4      .1       0
  367.89     .06       0  387.92      .1       0
Bank Sta=308.7,331.4
XS Rating Curve= 0 ,0
Exp/Cntr(USF)=0,0
Exp/Cntr=0.3,0.1

Type RM Length L Ch R = 1 ,2998    ,510.3,507.3,497.1
XS GIS Cut Line= 6
1593437.60170685437978.3379239291593546.44564925438016.260748342
1593608.84316225438081.8337799161593652.55862601438144.447171763
1593699.06968784438232.9735695121593817.15705009438460.392734095
#Sta/Elev= 30
       0  744.24    11.1  737.46      31  732.31   123.5  691.46   176.4  680.01
   218.5  667.66   250.3  655.15   281.9  653.05   290.8  650.83   305.6  652.88
  325.29649.3032   331.9  648.68   344.1  649.31     350  650.97   358.9  659.66
   379.6  669.67   401.8  675.44   417.7  682.68   421.2  687.83   431.2  707.81
     433  709.99   444.9  719.47   453.8  724.55   483.5  734.63   495.3  741.82
   516.9  747.77   561.9  776.83   590.3  787.19     616  798.67   638.4     815
#Mann= 3 ,-1,0
       0      .1       0  325.29    .045       0   344.1      .1       0
Bank Sta=325.29,344.1
XS Rating Curve= 0 ,0
Exp/Cntr(USF)=0,0
Exp/Cntr=0.3,0.1

Type RM Length L Ch R = 1 ,2490    ,495.4,493.3,488.6
XS GIS Cut Line= 6
1593128.69582859438497.0553904181593308.29586309438538.886015415
1593379.36855559438563.5680526791593540.73863967438631.278547168
1593627.09771892438650.8237836661593721.60081075 438664.02356042
#Sta/Elev= 30
       0   704.4    32.1  692.88    48.5  685.22    81.2  661.45    93.4   654.8
   106.6  650.06   130.6  646.61   247.8   643.4   264.8  641.92   282.2  645.23
   290.9  640.21  308.71639.0126   316.9  638.19   322.1  639.01   329.9  642.69
   342.9  643.56   351.6  646.54   390.7  676.54     395  681.45     408  704.96
   417.2  717.07   425.3  724.29   441.9  734.12   458.6  749.45   487.4  770.94
   552.5  797.45   568.7  802.96   588.9  813.72     601  822.14   618.6  827.41
#Mann= 5 ,-1,0
       0      .1       0  224.44     .05       0  308.71    .045       0
   322.1     .05       0  329.68      .1       0
Bank Sta=308.71,322.1
XS Rating Curve= 0 ,0
Exp/Cntr(USF)=0,0
Exp/Cntr=0.3,0.1

Type RM Length L Ch R = 1 ,1997    ,497.6,497,494.8
XS GIS Cut Line= 6
1593110.91863318439091.9423240131593204.57494192439085.390171751
1593291.83001676439078.8475339261593541.12971501439060.151377082
1593628.38478984439053.6067707541593721.80159776439045.650749922
#Sta/Elev= 30
       0  780.07    21.2  770.21    37.3  766.73    61.3  758.31    69.4  753.57
   105.5  716.87   109.5  710.38   117.5   693.1   121.5   686.8   137.5  673.97
   153.6  665.55   161.6  658.05   181.7  643.87   189.7  642.11   221.8  640.66
   225.8  639.41   233.8  634.01   237.8  633.61   253.9  635.83   269.9  640.97
  285.07634.3711     302  634.35   346.1  637.34   390.3  646.72   418.3  649.18
   482.3  670.41   498.6  674.01   522.6  684.55   550.7  698.97   612.6  721.21
#Mann= 5 ,-1,0
       0      .1       0  133.89     .06       0  231.39      .1       0
  285.07    .045       0     302      .1       0
Bank Sta=285.07,302
XS Rating Curve= 0 ,0
Exp/Cntr(USF)=0,0
Exp/Cntr=0.3,0.1

Type RM Length L Ch R = 1 ,1500    ,252.9,254.4,253
XS GIS Cut Line= 6
1593253.04991059439565.387571335  1593348.279707439546.099552169
1593435.95800935439539.2573742571593510.45917268439530.619924337
1593609.79361968439519.1025589261593864.33871426439489.590150759
#Sta/Elev= 30
       0   720.2    24.4  694.74      44  678.73    56.2  672.74    68.4  663.91
    80.7  659.27      97   649.2     109  644.79   121.1  638.63   129.1  637.39
   193.3  638.03   229.6  635.86   265.8  630.12   281.9  630.47     294  632.49
     302  630.13   306.1  629.38  311.08630.1268   326.2  632.94   342.3  640.21
   354.4   641.6   358.4  643.09   374.5  650.02   402.7  664.65     419  675.16
   483.2  700.67   507.4  708.71   575.9  727.62     596  734.56   616.4  743.82
#Mann= 6 ,-1,0
       0      .1       0      90     .06       0  195.11     .08       0
  290.11      .1       0     302    .045       0  311.08      .1       0
Bank Sta=302,311.08
XS Rating Curve= 0 ,0
Exp/Cntr(USF)=0,0
Exp/Cntr=0.3,0.1

Type RM Length L Ch R = 1 ,1246    ,228.5,234.7,243.3
BEGIN DESCRIPTION:
Structure XS 4
END DESCRIPTION:
XS GIS Cut Line= 2
1593374.78689948439760.7445945521593870.85054538439728.480292379
#Sta/Elev= 30
       0  702.44    13.4  692.11      24  680.89    29.4  676.33    35.3  673.85
    61.5  668.65    65.5  667.04    85.5  657.82   109.6  640.18   117.6  638.29
   137.6     637   145.6  628.74  148.34627.7331   157.7  626.92  162.98627.7401
   173.7  629.95   189.7  628.41   213.8  630.46   306.3  629.73     322  630.58
     342  638.11   366.1  644.36   386.1   653.1   404.2   658.3   446.3  674.27
   458.3  680.41   466.3  685.79   482.3  702.64   486.4  705.97   497.1  712.37
#Mann= 5 ,-1,0
       0      .1       0      70     .06       0  148.34    .045       0
  162.98     .06       0     170      .1       0
Bank Sta=148.34,162.98
XS Rating Curve= 0 ,0
Exp/Cntr(USF)=0,0
Exp/Cntr=0.3,0.1

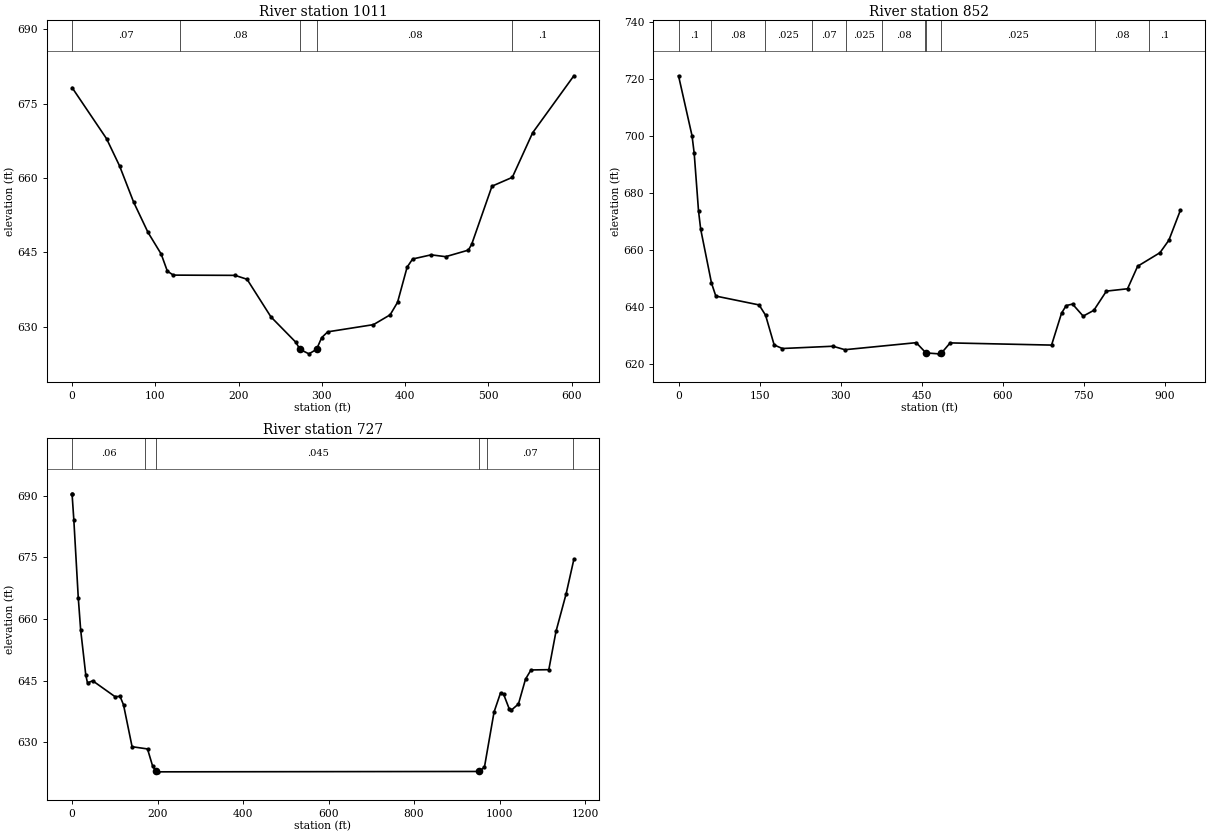
Type RM Length L Ch R = 1 ,1011    ,159.2,159.2,159.2
BEGIN DESCRIPTION:
Structure XS 3
END DESCRIPTION:
XS GIS Cut Line= 5
1593384.45126789439805.8547269821593596.05718552439944.665704319
1593643.16934247439983.2466297261593747.44369106440083.720563628
1593888.69208094440057.351504553
#Sta/Elev= 30
       0  678.24    41.4  667.93      57  662.45    73.9  655.14    91.2  649.02
     107  644.66   114.4  641.21   121.6  640.41   195.7  640.36   210.1  639.57
   238.8  631.98   268.7  626.86273.7049625.4205   284.4  624.53293.5328625.4314
   299.7   627.8     307  628.97   361.9  630.42   381.9   632.4   390.8  634.92
   402.3  642.02   408.9  643.66   431.1   644.5   448.6  644.13   475.8  645.45
   479.8  646.62   504.2  658.35   528.6  660.13     553  669.12   602.5  680.62
#Mann= 5 ,-1,0
       0     .07       0     130     .08       0273.7049    .045       0
293.5328     .08       0  528.77      .1       0
Bank Sta=273.7049,293.5328
XS Rating Curve= 0 ,0
Exp/Cntr(USF)=0,0
Exp/Cntr=0.3,0.1

Type RM Length L Ch R = 1 ,852     ,124.4,124.4,124.4
BEGIN DESCRIPTION:
Structure XS 2
END DESCRIPTION:
XS GIS Cut Line= 6
1593277.89930304439723.5129257511593282.04585743439900.478132299
1593429.53388215440002.6565684621593559.40418029440123.250416737
1593661.82865486440241.4999181551593892.59478596440182.013933055
#Sta/Elev= 30
       0  721.23      25  700.16      29     694      37  673.76      41  667.38
      61  648.46      69   643.9   149.1  640.79   161.1  637.17     177  626.74
   192.1  625.49   285.8  626.29   307.9  625.07   439.9  627.54   457.9  623.95
   481.2  623.62   486.6   623.9   502.7  627.46   690.4  626.69   708.9  637.91
   717.5  640.57   729.2  641.08   748.9  636.86   768.6  638.89   791.9  645.64
     831  646.46   849.7  654.37     891  659.12   907.5   663.5   928.7  673.97
#Mann= 11 ,-1,0
       0      .1       0      60     .08       0     160    .025       0
  247.01     .07       0  310.03    .025       0  376.67     .08       0
  456.25    .025       0   457.9    .045       0   486.6    .025       0
  770.38     .08       0  870.38      .1       0
Bank Sta=457.9,486.6
XS Rating Curve= 0 ,0
Exp/Cntr(USF)=0,0
Exp/Cntr=0.3,0.1

Type RM Length L Ch R = 1 ,727     ,,,
BEGIN DESCRIPTION:
Structure XS 1
END DESCRIPTION:
XS GIS Cut Line= 5
1593170.70293914 439708.492212491593151.68667922439970.271798612
1593377.79312748440137.6815790241593667.23235898440347.187577242
1593928.02670188440267.259045212
#Sta/Elev= 30
       0  690.44       0  690.39     4.1  684.13    14.5  665.16    20.1  657.35
    32.1  646.35    36.1  644.43    48.2  644.96   100.3  641.11   112.3  641.16
   120.4  639.09   140.4  628.92   176.5  628.38   188.5  624.19   196.6  622.91
   200.6  622.81   952.7   622.9   964.8     624   987.2  637.36  1002.4  642.02
  1009.6  641.67  1022.4  638.21  1027.5  637.81  1044.3  639.31  1060.8  645.36
  1073.6  647.59  1115.3  647.66  1132.1  656.96  1155.9  666.14  1173.9  674.49
#Mann= 6 ,-1,0
       0     .06       0     170    .025       0   196.6    .045       0
   952.7    .025       0  971.11     .07       0 1171.11      .1       0
Bank Sta=196.6,952.7
XS Rating Curve= 0 ,0
Exp/Cntr(USF)=0,0
Exp/Cntr=0.3,0.1
LCMann Table=0

Chan Stop Cuts=-1
Use User Specified Reach Order=0
Composite Channel Slope=5